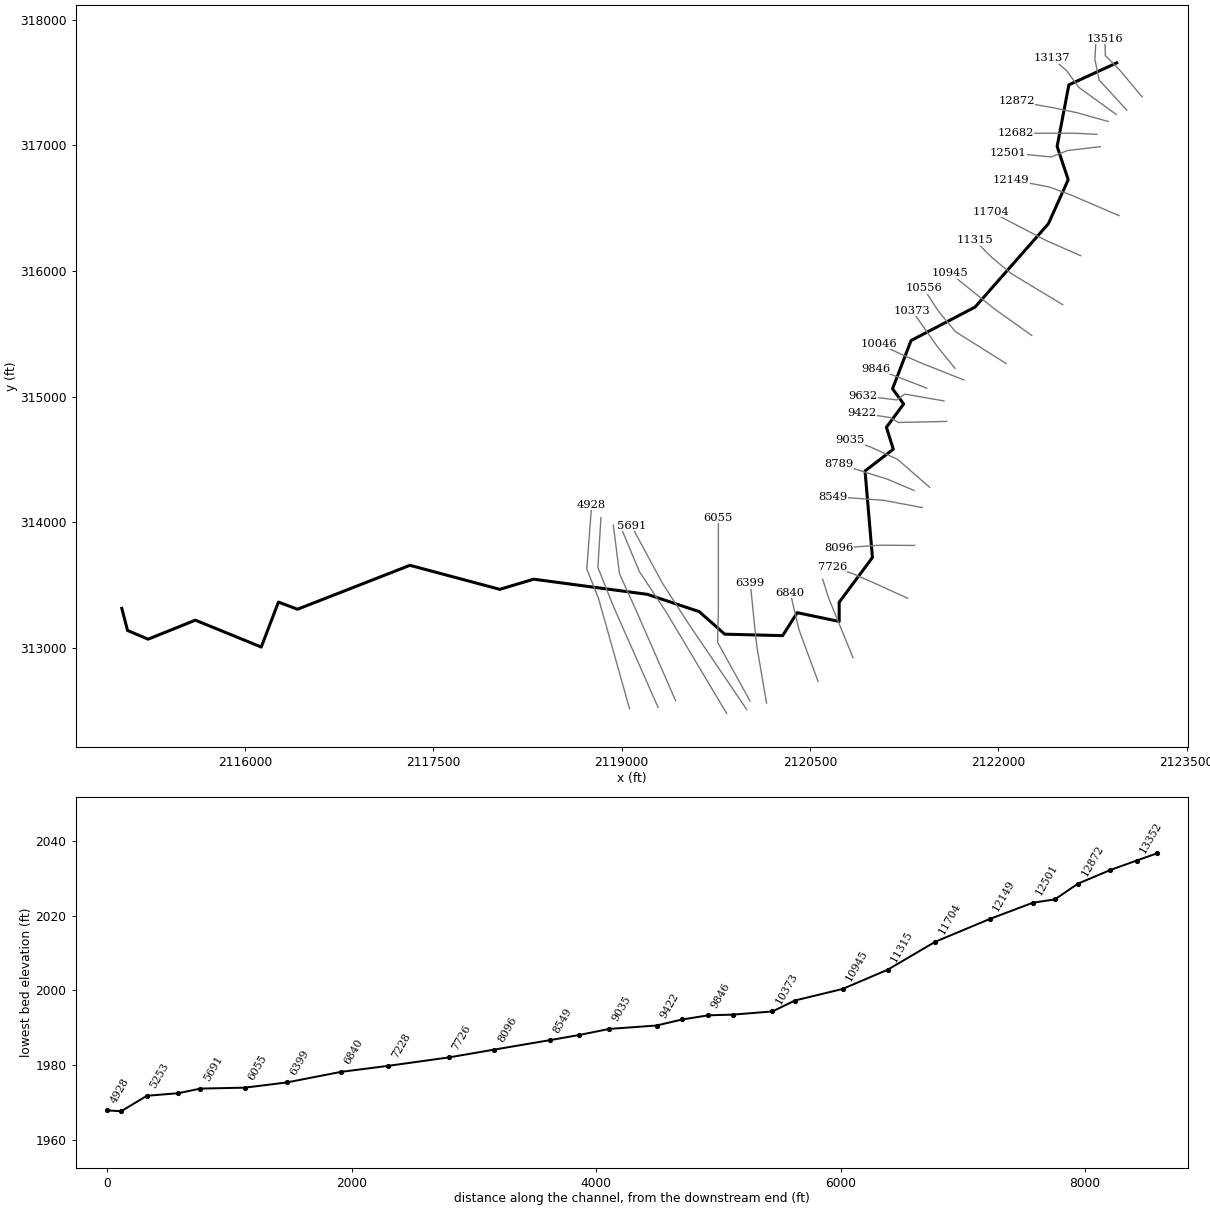
--- MLGNCKTR3.prj (project) ---

Proj Title=MLGNCKTR3
Current Plan=p01
Default Exp/Contr=0,0
English Units
Geom File=g01
Flow File=f01
Plan File=p01
BEGIN DESCRIPTION:
Stream Name- Milligan Creek Tributary 3
Flood Zone: Zone A
Greenbrier County, WV
County-Wide Study
WVDHSEM-2018-3, Flood Risk Project
HEC-RAS Version: 5.0.7
General Notes:
For the Hydrology Regression was used.
END DESCRIPTION:
DSS File=dss
DSS Export Rating Curves= 0
DSS Export Rating Curve Sorted= 0
DSS Export Volume Flow Curves= 0
DXF Filename=..\..\H1\MEADOWRV4\MEADOWRV4.
DXF OffsetX= 0
DXF OffsetY= 0
DXF ScaleX= 0
DXF ScaleY= 0

--- MLGNCKTR3.p01 (plan) ---

Plan Title=Floodplain
Program Version=5.07
Short Identifier=Floodplain
Geom File=g01
Flow File=f01
Subcritical Flow
K Sum by GR= 0
Std Step Tol= 0.01
Critical Tol= 0.01
Num of Std Step Trials= 20
Max Error Tol= 0.3
Flow Tol Ratio= 0.001
Split Flow NTrial= 30
Split Flow Tol= 0.02
Split Flow Ratio= 0.02
Log Output Level= 0
Friction Slope Method= 1
Unsteady Friction Slope Method= 2
Unsteady Bridges Friction Slope Method= 1
Parabolic Critical Depth
Global Vel Dist= 0 , 0 , 0
Global Log Level= 0
CheckData=True
Encroach Param=-1 ,0,0, 0
Computation Interval=0.1SEC
Output Interval=1MIN
Instantaneous Interval=Max Profile
Mapping Interval=1HOUR
Computation Time Step Use Courant=        0
Computation Time Step Use Time Series=    0
Computation Time Step Count To Double=0
Computation Time Step Max Doubling=0
Computation Time Step Max Halving=0
Computation Time Step Residence Courant=0
Run HTab= 0
Run UNet= 0
Run Sediment= 0
Run PostProcess= 0
Run WQNet= 0
Run RASMapper= 0
UNET Theta= 0
UNET Theta Warmup= 0
UNET ZTol= 0
UNET ZSATol= 0
UNET MxIter= 0
UNET Max Iter WO Improvement= 0
UNET MaxInSteps= 0
UNET DtIC= 0
UNET DtMin= 0
UNET MaxCRTS= 0
UNET WFStab= 0
UNET SFStab= 0
UNET WFX= 1
UNET SFX= 1
UNET 1D Methodology=Finite Difference
UNET DSS MLevel= 1
UNET Pardiso=0
UNET DZMax Abort= 0
UNET Use Existing IB Tables= 0
UNET Froude Reduction=False
UNET Froude Limit= 0
UNET Froude Power= 0
UNET D1 Cores= 0
UNET D2 Coriolis=0
UNET D2 Cores= 0
UNET D2 Theta= 1
UNET D2 Theta Warmup= 1
UNET D2 Z Tol= 0.01
UNET D2 Volume Tol= 0.01
UNET D2 Max Iterations= 20
UNET D2 Equation= 0
UNET D2 RampUpFraction=0.1
UNET D2 TimeSlices= 1
UNET D2 BCVolumeCheck=0
UNET D1D2 MaxIter= 0
UNET D1D2 ZTol=0.01
UNET D1D2 QTol=0.1
UNET D1D2 MinQTol=1
DSS File=dss
Write IC File= 0
Write IC File at Fixed DateTime=0
Write IC File at Sim End=0
Echo Input=False
Echo Parameters=False
Echo Output=False
Write Detailed= 0
HDF Write Warmup=0
HDF Write Time Slices=0
HDF Flush=0
HDF Face Node Velocities=0
HDF Compression= 1
HDF Chunk Size= 1
HDF Spatial Parts= 1
HDF Use Max Rows=0
HDF Fixed Rows= 1
Calibration Method= 0
Calibration Iterations= 20
Calibration Max Change=0.05
Calibration Tolerance=0.2
Calibration Maximum=1.5
Calibration Minimum=0.5
Calibration Optimization Method= 1
WQ AD Non Conservative
WQ ULTIMATE=-1
WQ Max Comp Step=1HOUR
WQ Output Interval=15MIN
WQ Output Selected Increments= 0
WQ Output face flow=0
WQ Output face velocity=0
WQ Output face area=0
WQ Output face dispersion=0
WQ Output cell volume=0
WQ Output cell surface area=0
WQ Output cell continuity=0
WQ Output cumulative cell continuity=0
WQ Output face conc=0
WQ Output face dconc_dx=0
WQ Output face courant=0
WQ Output face peclet=0
WQ Output face adv mass=0
WQ Output face disp mass=0
WQ Output cell mass=0
WQ Output cell source sink temp=0
WQ Output nsm pathways=0
WQ Output nsm derived pathways=0
WQ Output MaxMinRange=-1
WQ Daily Max Min Mean=-1
WQ Daily Range=0
WQ Daily Time=0
WQ Create Restart=0
WQ Fixed Restart=0
WQ System Summary=0
WQ Write To DSS=0
WQ Use Fixed Temperature=0
Sorting and Armoring Iterations= 10
XS Update Threshold= 0.02
Bed Roughness Predictor= 0
Hydraulics Update Threshold= 0.02
Energy Slope Method= 1
Volume Change Method= 1
Sediment Retention Method= 0
XS Weighting Method= 0
Number of US Weighted Cross Sections= 1
Number of DS Weighted Cross Sections= 1
Upstream XS Weight=0
Main XS Weight=1
Downstream XS Weight=0
Number of DS XS's Weighted with US Boundary= 1
Upstream Boundary Weight= 1
Weight of XSs Associated with US Boundary= 0
Number of US XS's Weighted with DS Boundary= 1
Downstream Boundary Weight= 0.5
Weight of XSs Associated with DS Boundary= 0.5
Percentile Method= 0
Sediment Output Level= 3
Mass or Volume Output= 0
Output Increment Type= 1
Profile and TS Output Increment= 1
XS Output Flag= 0
XS Output Increment= 10
Write Gradation File= 0
Read Gradation Hotstart= 0
Write HDF5 File= 1
Write Binary Output= 1
Write DSS Sediment File= 0
SV Curve= 0
Specific Gage Flag= 0

--- MLGNCKTR3.f01 (steady flow) ---

Flow Title=MasterFlow
Program Version=5.07
Number of Profiles= 6
Profile Names=f1p,f10p,f4p,f2p,f02p,f1pplus
River Rch & RM=MLGNCKTR3,Main            ,13516
    1790     990    1290    1530    2450    2650
River Rch & RM=MLGNCKTR3,Main            ,9632
    2060    1140    1480    1760    2810    3040
Boundary for River Rch & Prof#=MLGNCKTR3,Main            , 1
Up Type= 0
Dn Type= 3
Dn Slope=0.00401
Boundary for River Rch & Prof#=MLGNCKTR3,Main            , 2
Up Type= 0
Dn Type= 3
Dn Slope=0.00401
Boundary for River Rch & Prof#=MLGNCKTR3,Main            , 3
Up Type= 0
Dn Type= 3
Dn Slope=0.00401
Boundary for River Rch & Prof#=MLGNCKTR3,Main            , 4
Up Type= 0
Dn Type= 3
Dn Slope=0.00401
Boundary for River Rch & Prof#=MLGNCKTR3,Main            , 5
Up Type= 0
Dn Type= 3
Dn Slope=0.00401
Boundary for River Rch & Prof#=MLGNCKTR3,Main            , 6
Up Type= 0
Dn Type= 3
Dn Slope=0.00401
DSS Import GetInterval= 0
DSS Import GetPeak= 0
DSS Import FillOption= 0

--- MLGNCKTR3.g01 (geometry) ---

Geom Title=MasterGeometry
Program Version=5.07

River Reach=MLGNCKTR3       ,Main
Reach XY= 30
     2122941.967      317657.776     2122561.001      317482.841
      2122467.54      316992.419     2122555.714      316727.996
     2122398.172      316377.177     2121814.648      315713.854
      2121304.48      315446.896     2121156.911      315062.731
      2121245.43      314941.813      2121108.32      314756.456
     2121162.981      314581.739     2120937.958      314408.098
     2120997.007      313719.483     2120732.123      313363.077
     2120732.175       313210.07     2120397.863      313280.015
     2120281.818      313097.059      2119820.57      313108.862
      2119618.22      313287.918      2119205.02      313425.803
     2118299.549      313546.595     2118029.514      313465.831
     2117313.981      313657.084     2116418.979      313307.343
     2116267.243      313364.355     2116130.373      313006.387
     2115605.692      313220.407     2115229.651      313068.844
     2115065.588      313138.115     2115019.804        313314.5

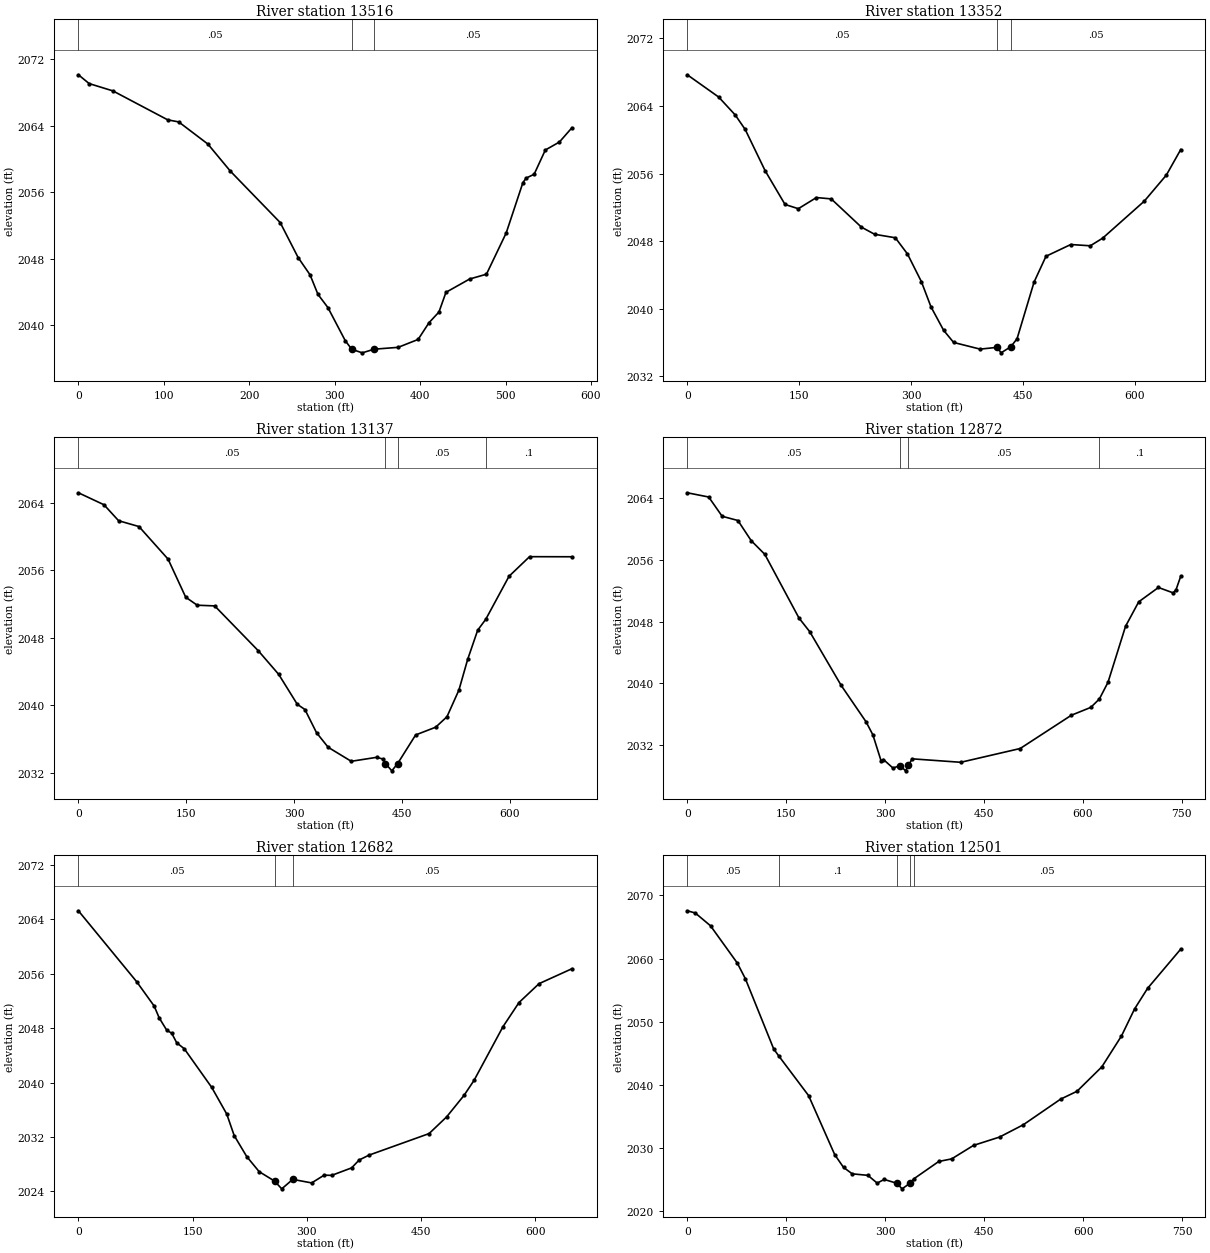
Type RM Length L Ch R = 1 ,13516   ,164.4,164.4,164.4
XS GIS Cut Line= 4
 2123144.8267959317386.4045645162122968.57028123317597.643288212
2122851.51442797317716.0446110472122847.47801924317851.937038393
#Sta/Elev= 30
       0 2070.13    12.6 2069.07    40.4 2068.19   104.5 2064.71   117.4 2064.46
   151.5  2061.8     178 2058.52   236.2 2052.35   257.2 2048.14   271.1 2046.07
   280.4 2043.71     292 2042.13   312.3 2038.15   319.9 2037.11   332.2 2036.68
   346.2 2037.12   374.2 2037.34   397.6 2038.29   410.4 2040.31     422 2041.59
   430.2 2043.96   457.9 2045.56   477.6 2046.14   500.7  2051.1   520.3 2057.17
   524.2 2057.71   533.4 2058.16   546.5 2061.08     563 2062.04577.5632 2063.75
#Mann= 3 , 0 , 0
       0     .05       0   319.9    .045       0   346.2     .05       0
Bank Sta=319.9,346.2
XS Rating Curve= 0 ,0
Exp/Cntr(USF)=0,0
Exp/Cntr=0.3,0.1

Type RM Length L Ch R = 1 ,13352   ,214.5,214.5,214.5
XS GIS Cut Line= 4
2123022.38906433317281.457937458 2122801.7320536317522.296991862
2122768.09531415317687.789749916 2122777.5136012 317853.28250797
#Sta/Elev= 30
       0 2067.69      42 2065.06    64.2 2062.94    77.6 2061.22   104.3 2056.34
     131 2052.34   148.8 2051.84   173.1 2053.16   192.9    2053   233.3 2049.66
   251.1 2048.81   278.8  2048.4   295.1 2046.48   313.7 2043.21   326.6 2040.22
   343.5 2037.45   356.9 2036.01   392.4 2035.22   415.3 2035.43   420.5 2034.78
  433.482035.497   441.9 2036.44   464.7 2043.15   480.7 2046.21   513.9  2047.6
   540.1 2047.45   556.6 2048.35   612.4 2052.73     642 2055.82661.2759 2058.84
#Mann= 3 , 0 , 0
       0     .05       0   415.3    .045       0  433.48     .05       0
Bank Sta=415.3,433.48
XS Rating Curve= 0 ,0
Exp/Cntr(USF)=0,0
Exp/Cntr=0.3,0.1

Type RM Length L Ch R = 1 ,13137   ,265.1,265.1,265.1
XS GIS Cut Line= 4
2122937.62448094317247.8211980162122641.62117385317461.750860866
2122544.74736426317593.6068794792122426.34604142 317697.20803696
#Sta/Elev= 30
       0 2065.19    35.6 2063.77    55.9 2061.88    84.2 2061.19   124.7 2057.33
   149.2 2052.82   165.2 2051.87   189.5 2051.79   250.2 2046.47   278.5 2043.68
   304.3 2040.14     315 2039.51   331.1 2036.77   347.3 2035.04   379.4 2033.38
   414.6 2033.85   423.9 2033.64  426.992033.115   435.8 2032.25  443.922033.115
   468.9  2036.5   496.8 2037.42   512.5 2038.66   529.1 2041.82   541.3 2045.46
   555.2 2048.91  566.432050.201   598.8  2055.3   627.3 2057.62686.1625 2057.61
#Mann= 4 ,-1 , 0
       0     .05       0  426.99    .045       0  443.92     .05       0
  566.43      .1       0
Bank Sta=426.99,443.92
XS Rating Curve= 0 ,0
Exp/Cntr(USF)=0,0
Exp/Cntr=0.3,0.1

Type RM Length L Ch R = 1 ,12872   ,189.7,189.7,189.7
XS GIS Cut Line= 4
2122874.38741079317191.3114757532122624.13006934317261.275893792
2122425.00057185  317302.98545072122143.79743011317351.422355497
#Sta/Elev= 30
       0 2064.72    32.5 2064.17    52.9 2061.67    76.8 2061.12      97  2058.5
   117.6 2056.73   169.5 2048.45   185.8 2046.68   233.5  2039.7   271.2 2034.98
   281.6 2033.28   294.2 2029.86   297.6 2030.08   312.1 2028.97   323.1  2029.3
   331.1 2028.61  335.62 2029.32   341.1 2030.17   414.9 2029.72   505.1 2031.51
   582.7 2035.83   612.2 2036.85  625.242037.946   638.3 2040.11   664.9 2047.38
   684.9 2050.56   714.8 2052.42   737.2 2051.72   741.5 2052.13748.6484 2053.88
#Mann= 4 ,-1 , 0
       0     .05       0   323.1    .045       0  335.62     .05       0
  625.24      .1       0
Bank Sta=323.1,335.62
XS Rating Curve= 0 ,0
Exp/Cntr(USF)=0,0
Exp/Cntr=0.3,0.1

Type RM Length L Ch R = 1 ,12682   ,181.5,181.5,181.5
XS GIS Cut Line= 3
2122785.05058984317088.7776139182122608.94008325317097.732385439
2122137.32211645317097.732385439
#Sta/Elev= 30
       0 2065.24    76.5 2054.82    99.5 2051.24   106.1  2049.5     116 2047.69
   122.5 2047.25   129.1 2045.84     139 2044.97   175.1 2039.28   194.8 2035.37
   204.6  2032.2     221 2029.13   237.4  2026.9   257.62025.523     267 2024.38
   281.5 2025.77   306.3 2025.25   322.7 2026.39   332.6 2026.36   358.8 2027.46
   368.7 2028.62   381.8 2029.34   460.5  2032.5   483.5 2034.95   506.5 2038.13
   519.6 2040.33   557.5  2048.2   578.6 2051.76   604.9 2054.53     648 2056.72
#Mann= 3 , 0 , 0
       0     .05       0   257.6    .045       0   281.5     .05       0
Bank Sta=257.6,281.5
XS Rating Curve= 0 ,0
Exp/Cntr(USF)=0,0
Exp/Cntr=0.3,0.1

Type RM Length L Ch R = 1 ,12501   ,351.9,351.9,351.9
XS GIS Cut Line= 4
2122812.49581022316990.8365086792122550.12924257316959.890708393
2122420.96416311316908.7628644412122077.86942081316942.399603883
#Sta/Elev= 30
       0 2067.57    12.1 2067.22    35.2 2065.19    75.8 2059.28    88.1 2056.78
     131 2045.65  138.282044.598   183.9 2038.25   223.5 2028.88   236.8 2026.87
     250 2025.85   273.7 2025.61   287.8 2024.38   298.4 2024.96   317.7 2024.35
   325.5 2023.47  337.43 2024.35  343.462025.066   381.1 2027.81   400.7 2028.22
   433.8 2030.36   473.2 2031.68   509.2 2033.63   565.7 2037.69   590.6 2038.94
   628.3 2042.82     658 2047.71   677.8 2051.99   697.6 2055.27 747.841 2061.49
#Mann= 5 ,-1 , 0
       0     .05       0  138.28      .1       0   317.7    .045       0
  337.43      .1       0  343.46     .05       0
Bank Sta=317.7,337.43
XS Rating Curve= 0 ,0
Exp/Cntr(USF)=0,0
Exp/Cntr=0.3,0.1

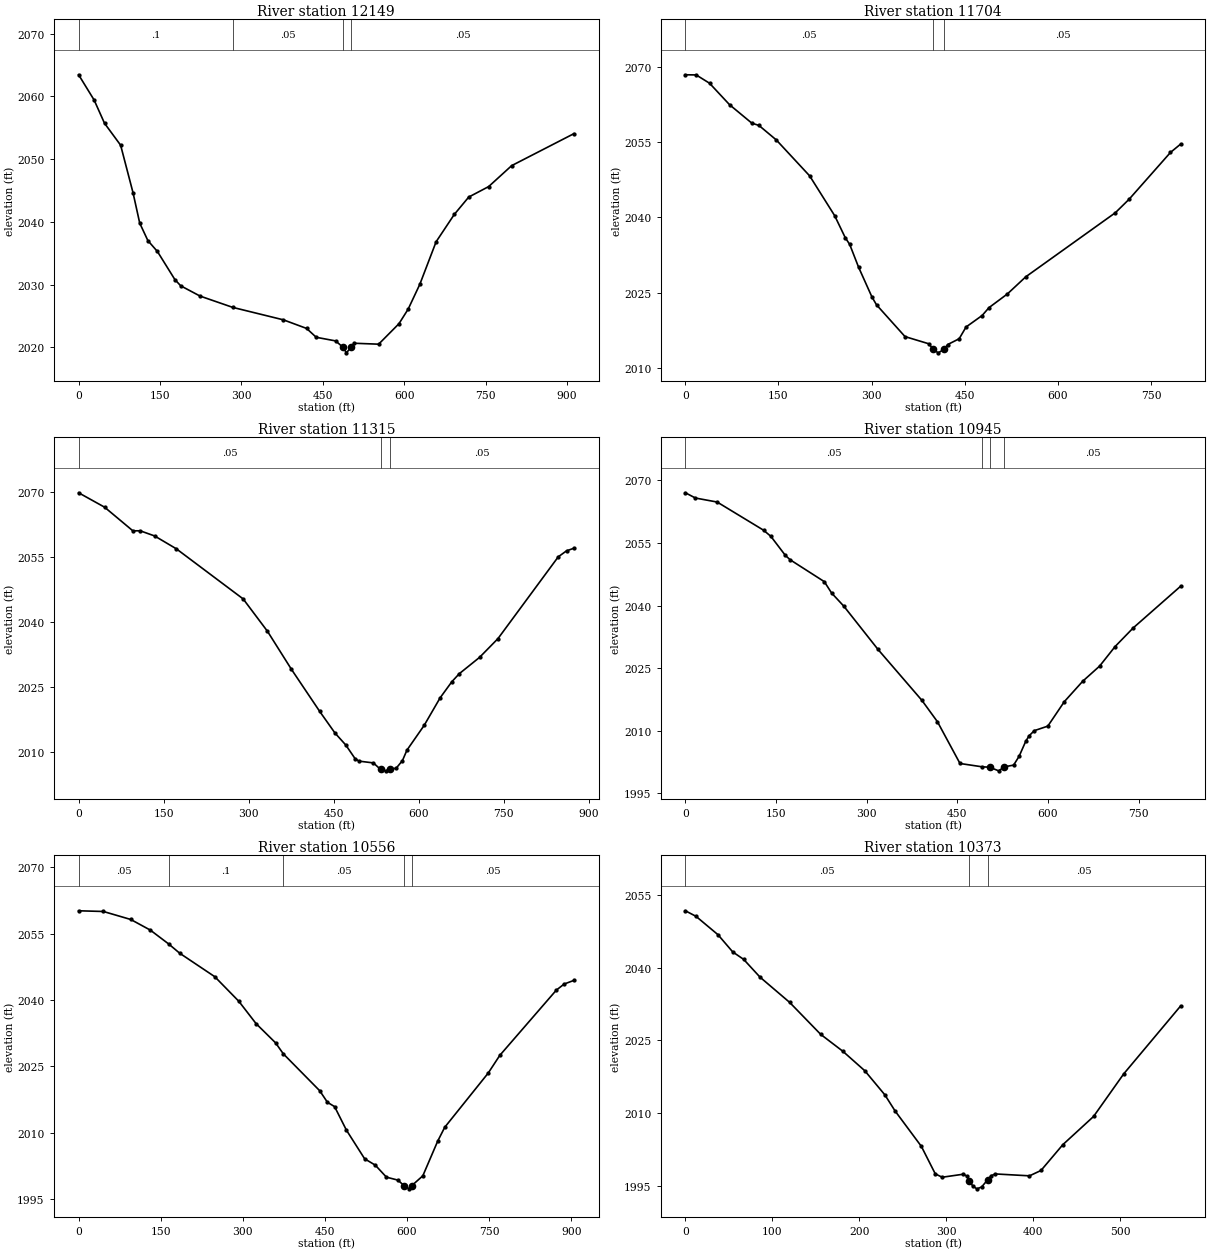
Type RM Length L Ch R = 1 ,12149   ,445.5,445.5,445.5
XS GIS Cut Line= 4
2122960.13018194316441.5416324532122578.08326482316605.803350441
2122402.74772315316670.4006552682122098.21757183316727.615410971
#Sta/Elev= 30
       0 2063.46    28.6 2059.43    47.7 2055.73    77.4 2052.23   100.2 2044.67
   112.6  2039.8   127.6 2037.02   145.2 2035.28   177.4  2030.8   188.1 2029.81
   223.8 2028.17  284.072026.366   377.4 2024.38   420.1 2023.01   437.8  2021.6
   473.6 2021.02  487.412019.986   493.5 2019.12  501.732019.986   507.5 2020.65
   552.8  2020.5   590.2 2023.76   607.2 2026.09   628.7 2030.05   658.7 2036.83
   692.1 2041.18   718.8 2043.96   755.5 2045.63   797.9 2048.97912.5775 2054.07
#Mann= 4 ,-1 , 0
       0      .1       0  284.07     .05       0  487.41    .045       0
  501.73     .05       0
Bank Sta=487.41,501.73
XS Rating Curve= 0 ,0
Exp/Cntr(USF)=0,0
Exp/Cntr=0.3,0.1

Type RM Length L Ch R = 1 ,11704   ,389.1,389.1,389.1
XS GIS Cut Line= 3
2122655.60003062316122.246382881 2122378.7544385316244.058443411
2121939.49276568316472.917466226
#Sta/Elev= 30
       0 2068.36    17.4 2068.33    38.9 2066.68    71.2  2062.4     107 2058.74
   118.5 2058.28   146.4  2055.4   200.2 2048.24   240.5 2040.32   257.5 2035.95
   264.7  2034.6     279 2030.07   300.5 2024.15   307.9 2022.58   353.8 2016.26
   392.7 2014.81  398.462013.771   407.3 2013.03  417.152013.771   422.5 2014.68
     441 2015.83   452.1 2018.17     478 2020.46   489.1 2022.03   518.7 2024.75
   548.3 2028.16   692.6 2040.91   714.8  2043.6   781.4 2052.91797.7646 2054.57
#Mann= 3 ,-1 , 0
       0     .05       0  398.46    .045       0  417.15     .05       0
Bank Sta=398.46,417.15
XS Rating Curve= 0 ,0
Exp/Cntr(USF)=0,0
Exp/Cntr=0.3,0.1

Type RM Length L Ch R = 1 ,11315   ,369.4,369.4,369.4
XS GIS Cut Line= 4
2122511.64032272 315732.816916642122101.90884639315980.132312262
2121945.02967752316111.1725591962121810.29815603316245.904080692
#Sta/Elev= 30
       0 2069.84    45.8 2066.51    95.7 2061.04   108.6 2061.05     134 2059.86
   172.3 2056.89   290.2  2045.3   333.1 2037.81   375.4 2029.01   425.2 2019.29
   452.1  2014.3   471.2 2011.52   487.5 2008.39   494.3  2007.8   519.9 2007.38
   532.5 2005.88   541.8 2005.55   548.8 2005.89   560.1 2006.16   571.1 2007.91
   579.1 2010.34   609.4 2016.05   637.6 2022.43   658.3 2026.16   671.3    2028
   707.1 2031.78   739.6 2036.12     846 2055.04   860.5 2056.41873.5334 2057.02
#Mann= 3 , 0 , 0
       0     .05       0   532.5    .045       0   548.8     .05       0
Bank Sta=532.5,548.8
XS Rating Curve= 0 ,0
Exp/Cntr(USF)=0,0
Exp/Cntr=0.3,0.1

Type RM Length L Ch R = 1 ,10945   ,389.7,389.7,389.7
XS GIS Cut Line= 3
2122266.17056437315487.3471582982121967.17732489315699.595445586
2121614.66060427315983.823586824
#Sta/Elev= 30
       0 2067.01    16.7 2065.75    52.6 2064.79   129.3 2058.05   141.4 2056.58
   165.5    2052   173.6 2050.94   229.9 2045.72     242 2042.99   262.2 2039.84
   318.7 2029.49   391.4 2017.28   417.1 2012.16   454.4 2002.16  490.952001.365
   503.4 2001.27   518.4  2000.4  527.862001.366   543.1 2001.77   552.2 2003.88
   563.1 2007.45   568.7 2008.79   577.4 2010.03   599.7 2011.11     627 2016.97
   657.5 2021.87   685.4 2025.49     711 2030.17   740.8 2034.61819.4977 2044.63
#Mann= 4 ,-1 , 0
       0     .05       0  490.95    .045       0   503.4    .045       0
  527.86     .05       0
Bank Sta=503.4,527.86
XS Rating Curve= 0 ,0
Exp/Cntr(USF)=0,0
Exp/Cntr=0.3,0.1

Type RM Length L Ch R = 1 ,10556   ,183.2,183.2,183.2
XS GIS Cut Line= 4
2122061.30482621315264.025047326  2121658.955899 315516.87735479
2121526.07001479315675.6021609362121404.25795426315862.011526293
#Sta/Elev= 30
       0 2060.19    45.3 2060.03    95.3 2058.22     131 2055.82   164.52052.689
   184.8 2050.58   248.8 2045.28   292.8 2039.71   324.3 2034.66   359.8 2030.33
  374.022027.839   440.6 2019.48   454.6 2016.88   467.7  2015.9   489.2  2010.6
   522.6  2004.1     542 2002.67   562.4 1999.95   583.4 1999.28   594.31998.063
   604.1 1997.31  608.981998.064   628.9 2000.26   656.1 2008.11   668.9 2011.23
   748.4  2023.5   769.5 2027.49   872.9 2042.26   887.1 2043.62904.8925 2044.45
#Mann= 5 ,-1 , 0
       0     .05       0   164.5      .1       0  374.02     .05       0
   594.3    .045       0  608.98     .05       0
Bank Sta=594.3,608.98
XS Rating Curve= 0 ,0
Exp/Cntr(USF)=0,0
Exp/Cntr=0.3,0.1

Type RM Length L Ch R = 1 ,10373   ,326.2,326.2,326.2
XS GIS Cut Line= 3
2121653.76445428315226.1851374362121513.47303378315399.310720186
2121313.48313646315682.878485035
#Sta/Elev= 30
       0 2051.69    12.2 2050.55    37.5 2046.76    54.5 2043.21    67.1 2041.67
    85.9 2038.01   119.8 2032.84   155.7 2026.22   181.1 2022.75   206.4 2018.73
   229.5 2013.76   241.3 2010.43   271.5 2003.14   287.5 1997.48   295.4 1996.78
   319.6  1997.4   323.7 1997.03   326.51996.104   330.7 1994.95   335.4 1994.39
   340.8 1994.77   347.7 1996.24   351.9  1997.1   356.6 1997.46   395.9 1997.07
   409.1 1998.17   434.3  2003.5   469.6  2009.3   504.3 2018.08   569.8 2032.08
#Mann= 3 , 0 , 0
       0     .05       0   326.5    .045       0   347.7     .05       0
Bank Sta=326.5,347.7
XS Rating Curve= 0 ,0
Exp/Cntr(USF)=0,0
Exp/Cntr=0.3,0.1

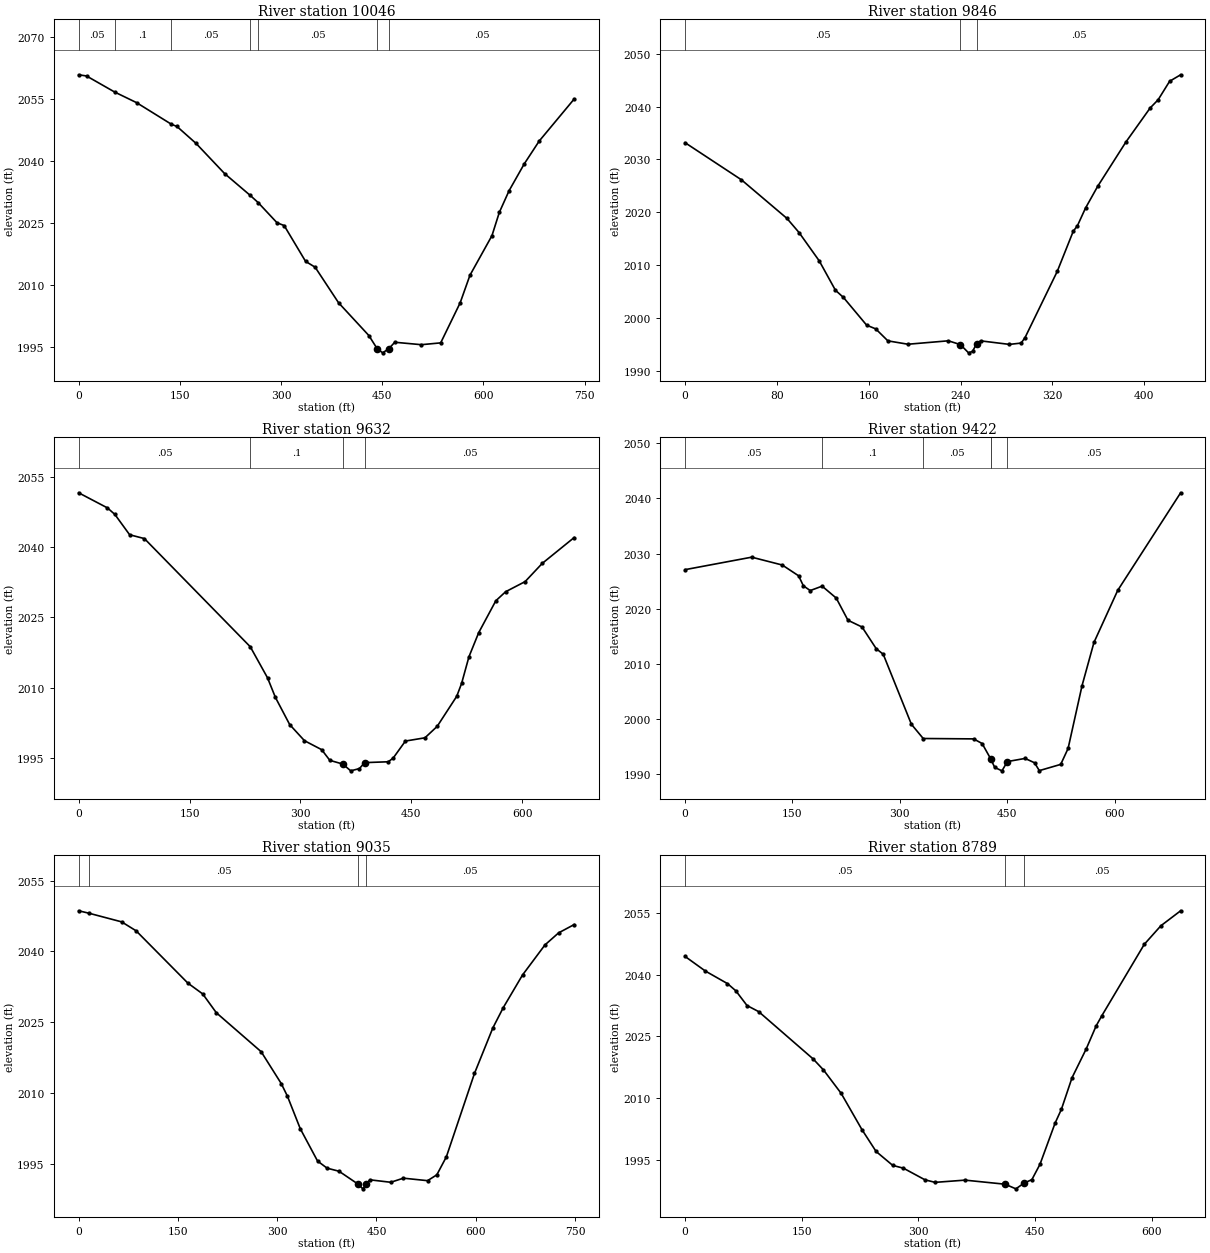
Type RM Length L Ch R = 1 ,10046   ,199,199,199
XS GIS Cut Line= 4
2121725.39884111315132.9848003922121385.80158145315267.716321887
 2121217.8485889315341.5418131182121049.89559635315420.904216191
#Sta/Elev= 30
       0 2060.76    11.7 2060.47   53.472056.583    85.8 2054.03  137.622048.785
   145.8 2048.26   174.1 2044.16   216.4 2036.87  254.532031.573  266.032029.873
   294.1 2024.98   304.7  2024.3   336.4 2015.65   350.6 2014.23   385.3 2005.64
   430.2 1997.72  442.361994.575   450.7 1993.53  460.061994.575   468.6 1996.09
     508  1995.5   536.7 1995.94   565.6 2005.64   580.1  2012.3   612.7 2021.86
   623.6 2027.48   638.1 2032.74   660.5  2039.2   682.7 2044.73734.5694  2054.9
#Mann= 7 ,-1 , 0
       0     .05       0   53.47      .1       0  137.62     .05       0
  254.53      .1       0  266.03     .05       0  442.36    .045       0
  460.06     .05       0
Bank Sta=442.36,460.06
XS Rating Curve= 0 ,0
Exp/Cntr(USF)=0,0
Exp/Cntr=0.3,0.1

Type RM Length L Ch R = 1 ,9846    ,214,214,214
XS GIS Cut Line= 2
2121429.89516624315067.9841738882121026.93044777315223.200213595
#Sta/Elev= 30
       0 2033.16    49.1 2026.13    88.8 2018.81    99.3 2016.14   116.9 2010.77
     131 2005.21     138 2003.84   158.2 1998.59   166.1 1997.89   176.7 1995.62
   194.2 1994.98   229.4 1995.63   239.9 1994.91     247 1993.35   250.5 1993.63
     254 1995.08   257.5 1995.62   282.6 1994.95   292.8  1995.2   296.2 1996.23
   324.3 2008.79   338.2 2016.37   341.9 2017.45   348.9 2020.77   359.5 2024.89
   384.1 2033.29   405.2 2039.73   412.2  2041.3   422.2  2044.8   431.8 2046.03
#Mann= 3 , 0 , 0
       0     .05       0   239.9    .045       0     254     .05       0
Bank Sta=239.9,254
XS Rating Curve= 0 ,0
Exp/Cntr(USF)=0,0
Exp/Cntr=0.3,0.1

Type RM Length L Ch R = 1 ,9632    ,209.3,209.3,209.3
XS GIS Cut Line= 4
 2121565.9135008314966.2664021972121255.30290155315020.274532627
 2121190.2042776314974.204737211 2120917.0340249315006.707818744
#Sta/Elev= 30
       0  2051.6  38.9832048.369  48.9732046.986  68.953 2042.64  88.934 2041.82
 232.126 2018.72 255.4372012.094 266.1232007.903 285.4072002.112 305.3881998.668
  328.66 1996.75 339.7241994.467 357.057 1993.69 367.9681992.231 379.7091992.713
 386.7971993.985 418.7781994.167 425.3861994.964 441.9051998.591 468.3371999.283
 484.8572001.723 511.2892008.142 517.8972010.897 527.8092016.581 541.0252021.737
 564.1532028.539 577.3692030.467   603.82032.636 626.9282036.521 670.1192042.044
#Mann= 4 ,-1 , 0
       0     .05       0 232.126      .1       0 357.057    .045       0
 386.797     .05       0
Bank Sta=357.057,386.797
XS Rating Curve= 0 ,0
Exp/Cntr(USF)=0,0
Exp/Cntr=0.3,0.1

Type RM Length L Ch R = 1 ,9422    ,387,387,387
XS GIS Cut Line= 4
2121587.66924307314802.8851882862121202.65946272314794.404796649
2121138.20848627314833.4145981822120909.23791205314869.032243061
#Sta/Elev= 30
       0 2027.08      93 2029.34   135.7 2027.92   158.6 2025.96   165.2 2024.15
   174.8 2023.29   191.4 2024.09   211.1 2021.93   227.5 2017.91   247.2 2016.68
   266.9 2012.77   276.8 2011.74   316.1 1999.06   332.6 1996.48     403 1996.41
   414.9 1995.57   426.8 1992.81   426.91992.775   432.5 1991.24   442.6 1990.62
   450.2  1992.3   474.9 1992.87   488.1 1992.08   494.8 1990.66   524.7 1991.79
     535 1994.68   554.5 2006.07   571.1 2013.88   604.3 2023.32   692.2 2041.01
#Mann= 6 ,-1 , 0
       0     .05       0   191.4      .1       0   332.6     .05       0
   426.8    .045       0   426.9    .045       0   450.2     .05       0
Bank Sta=426.9,450.2
XS Rating Curve= 0 ,0
Exp/Cntr(USF)=0,0
Exp/Cntr=0.3,0.1

Type RM Length L Ch R = 1 ,9035    ,245.9,245.9,245.9
XS GIS Cut Line= 4
2121451.83438194314278.6598102072121195.49587072314502.186991988
2120974.01939703314602.6716883852120816.11487412314651.888682539
#Sta/Elev= 30
       0 2048.62   15.342048.112      65 2046.27    86.8 2044.38   165.1 2033.29
   187.5    2031   208.1 2027.01   275.8 2018.76   306.1 2012.02   315.4 2009.36
   334.9 2002.44     361  1995.6   375.4 1994.09   393.4 1993.44  422.48 1990.68
   429.5 1989.71  434.171990.682   440.1 1991.62   471.6  1991.1   490.7 1991.97
   527.2 1991.44   541.2 1992.68   555.6 1996.49   598.1 2014.17   625.8 2023.79
   641.5 2028.08   670.7 2035.02   704.6 2041.39   725.2 2043.94748.7112  2045.7
#Mann= 4 ,-1 , 0
       0      .1       0   15.34     .05       0  422.48    .045       0
  434.17     .05       0
Bank Sta=422.48,434.17
XS Rating Curve= 0 ,0
Exp/Cntr(USF)=0,0
Exp/Cntr=0.3,0.1

Type RM Length L Ch R = 1 ,8789    ,240.5,240.5,240.5
XS GIS Cut Line= 3
2121328.40775567314253.0999654272121116.47816299314342.647680643
2120728.43806372314465.029558104
#Sta/Elev= 30
       0 2044.39    26.1 2040.85    54.5 2037.81    65.2 2036.07    79.6  2032.5
    94.6 2031.02   164.7 2019.54   177.9 2016.89   200.6 2011.22   227.3 2002.44
   245.5 1997.14   266.9 1993.76   280.7 1993.08   308.4 1990.26   321.4 1989.65
   359.8 1990.19   411.4  1989.2   425.2 1988.08   435.5 1989.44   445.8 1990.32
   456.2 1994.03   475.7 2004.05   483.7 2007.34   497.4 2015.01   515.7 2022.02
   528.4 2027.57   535.8 2030.06   590.3 2047.34   611.6 2051.83     637 2055.46
#Mann= 3 , 0 , 0
       0     .05       0   411.4    .045       0   435.5     .05       0
Bank Sta=411.4,435.5
XS Rating Curve= 0 ,0
Exp/Cntr(USF)=0,0
Exp/Cntr=0.3,0.1

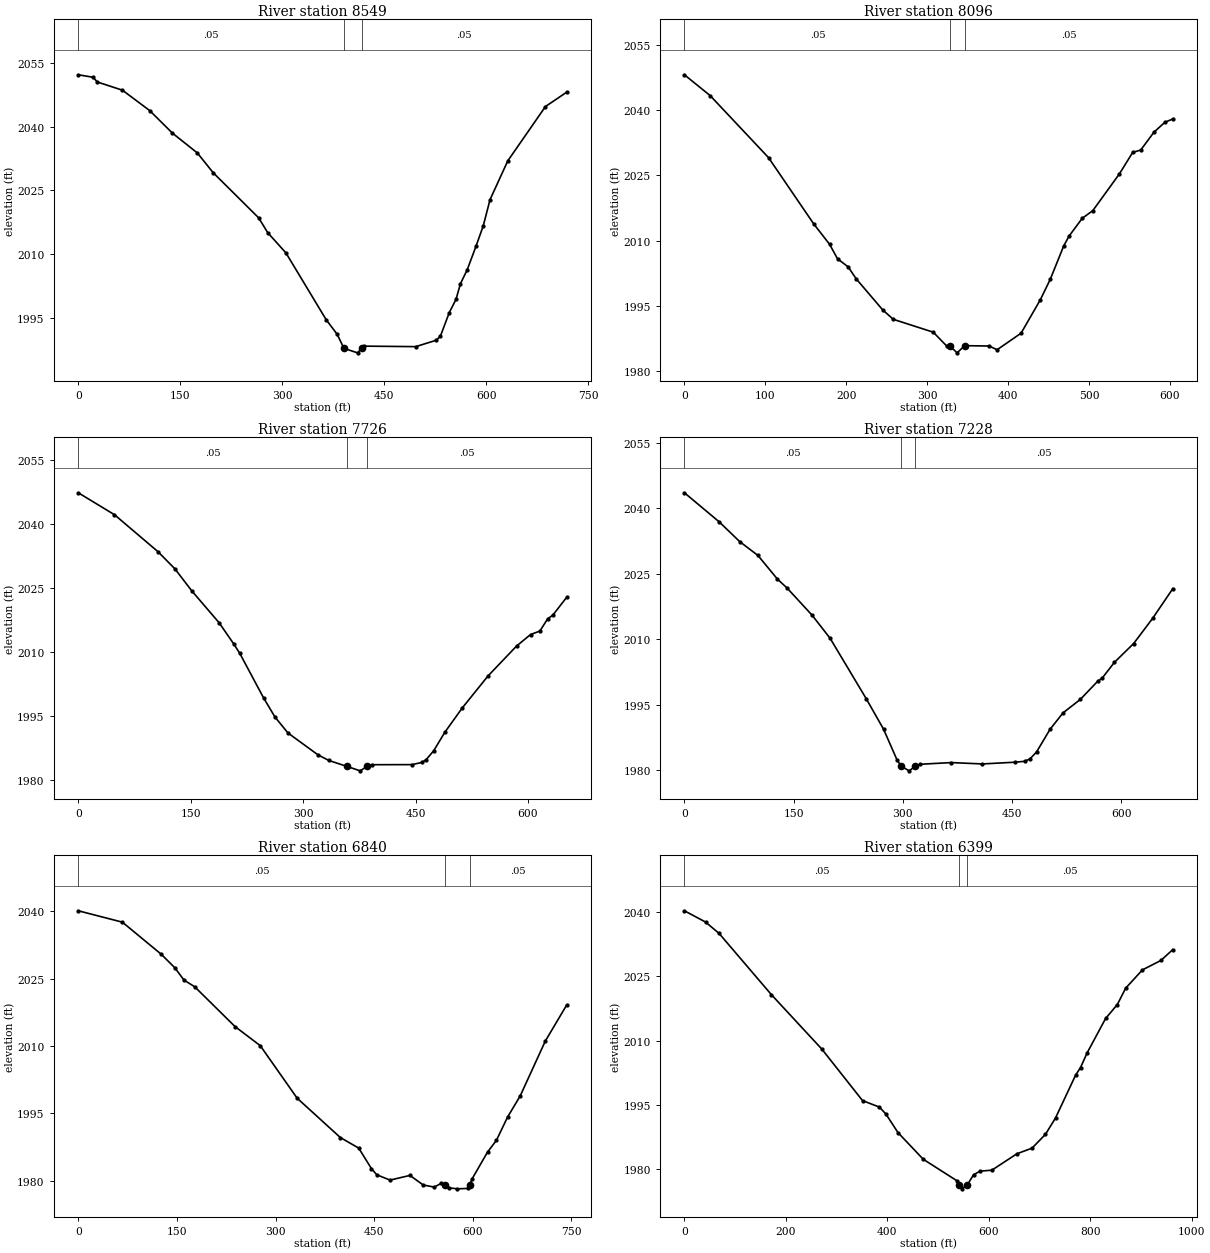
Type RM Length L Ch R = 1 ,8549    ,453.3,453.3,453.3
XS GIS Cut Line= 3
2121394.41455543314116.6538711182121090.90975815 314174.07369763
2120682.81884829314204.834318976
#Sta/Elev= 30
       0 2052.22    21.5 2051.64    28.2 2050.51    64.9 2048.59     105 2043.79
   138.3 2038.49   175.1  2033.8   198.4 2029.14   265.2 2018.52   278.6 2015.01
   305.3 2010.26   364.6 1994.49   380.8 1991.05   390.6 1987.76   410.6  1986.7
  416.681987.761   420.5 1988.28   496.2 1988.16   525.8 1989.64   532.4 1990.58
   545.5 1996.17   555.4 1999.29     562 2002.99   571.9 2006.27     585 2011.88
   595.5 2016.62   605.5 2022.81   631.6 2031.94     687 2044.74718.1373 2048.11
#Mann= 3 ,-1 , 0
       0     .05       0   390.6    .045       0  416.68     .05       0
Bank Sta=390.6,416.68
XS Rating Curve= 0 ,0
Exp/Cntr(USF)=0,0
Exp/Cntr=0.3,0.1

Type RM Length L Ch R = 1 ,8096    ,370,370,370
XS GIS Cut Line= 4
2121332.89331274313815.1997819262121056.04772062313817.250490016
2120850.97691165313802.8955333882120729.98513435313798.794117208
#Sta/Elev= 30
       0 2048.14    31.8 2043.35   103.9 2029.09   159.7 2013.86   179.4 2009.14
   189.2 2005.81   202.4 2003.94   212.2 2001.22     245 1994.06   258.1 1991.89
   307.5 1988.93   323.9 1985.79   328.6 1985.64     337 1984.18   346.3 1985.83
   376.5 1985.75   386.4 1984.89     416  1988.7   439.7 1996.35     452 2001.06
   468.6 2008.73   475.2 2011.01   491.6 2015.13   504.7  2016.9   537.6 2025.37
     554  2030.3   563.8 2030.82   580.2 2034.93   593.8 2037.23603.4871 2037.97
#Mann= 3 , 0 , 0
       0     .05       0   328.6    .045       0   346.3     .05       0
Bank Sta=328.6,346.3
XS Rating Curve= 0 ,0
Exp/Cntr(USF)=0,0
Exp/Cntr=0.3,0.1

Type RM Length L Ch R = 1 ,7726    ,497.9,497.9,497.9
XS GIS Cut Line= 4
2121277.52419431 313394.804623532121006.83072647313517.847108914
2120832.52053884313593.7233082352120676.66672402313644.991010478
#Sta/Elev= 30
       0  2047.4    48.3 2042.25   106.3 2033.57     129 2029.52   151.3 2024.39
     188 2016.85   207.9 2011.77   215.5 2009.67   247.5 1999.13   262.3 1994.76
   279.7 1990.99   319.9 1985.83   334.4 1984.52  358.691983.115   376.1 1982.09
  385.131983.116   391.4 1983.53   445.1 1983.55   458.3 1984.06   464.1 1984.72
   474.1 1986.79   489.1 1991.17   512.2 1996.85   546.7 2004.39   584.7  2011.4
   603.4 2014.11   615.8 2014.92   626.2  2017.8   633.1 2018.66651.5236 2022.84
#Mann= 3 ,-1 , 0
       0     .05       0  358.69    .045       0  385.13     .05       0
Bank Sta=358.69,385.13
XS Rating Curve= 0 ,0
Exp/Cntr(USF)=0,0
Exp/Cntr=0.3,0.1

Type RM Length L Ch R = 1 ,7228    ,387.4,387.4,387.4
XS GIS Cut Line= 3
2120842.77407929312921.0910548012120647.95681076 313396.85533162
 2120600.7905247313546.557022171
#Sta/Elev= 30
       0 2043.51    47.8 2036.85    76.1 2032.31     101 2029.16   127.7 2023.76
   141.1 2021.69   175.5 2015.46   200.2 2010.18   249.9 1996.33   273.6 1989.38
   292.4 1982.23  298.21 1980.86   308.8 1979.83  317.06 1980.86   324.3 1981.34
   366.6 1981.72   409.5 1981.41   454.7 1981.81   467.3 1982.01   474.8 1982.56
   483.8 1984.14   502.5 1989.37   520.3 1993.11   543.9 1996.17   567.7 2000.32
   574.2  2001.1   590.9 2004.69   617.3 2008.99   643.3 2014.74671.0626 2021.55
#Mann= 3 ,-1 , 0
       0     .05       0  298.21    .045       0  317.06     .05       0
Bank Sta=298.21,317.06
XS Rating Curve= 0 ,0
Exp/Cntr(USF)=0,0
Exp/Cntr=0.3,0.1

Type RM Length L Ch R = 1 ,6840    ,441.3,441.3,441.3
XS GIS Cut Line= 3
2120563.87777908312732.4259105452120412.12538044313144.618236582
2120342.40130539313439.920201504
#Sta/Elev= 30
       0 2040.15    67.1 2037.61   126.2 2030.46   146.8 2027.46   160.8 2024.71
     177 2023.23   238.3 2014.37   276.7 2010.11   332.9 1998.39   398.5 1989.64
   426.5 1987.28   445.7 1982.74   453.9 1981.34   474.1 1980.16   504.4  1981.2
   524.5 1979.07   541.2  1978.6   552.1 1979.44   557.5 1979.06     563 1978.44
   576.6 1978.21   592.1  1978.3   595.5 1979.13   598.8 1980.41   622.4 1986.41
   635.9 1989.02   652.8 1994.19   672.1 1998.93   710.2 2011.12742.6611 2019.14
#Mann= 3 , 0 , 0
       0     .05       0   557.5    .045       0   595.5     .05       0
Bank Sta=557.5,595.5
XS Rating Curve= 0 ,0
Exp/Cntr(USF)=0,0
Exp/Cntr=0.3,0.1

Type RM Length L Ch R = 1 ,6399    ,344.2,344.2,344.2
XS GIS Cut Line= 4
2120153.73616114312560.1664310072120077.85996182 313003.11937839
2120057.35288092313187.6831064672120024.54155148313513.745692735
#Sta/Elev= 30
       0 2040.33    41.6  2037.7    68.2 2035.06   171.4 2020.75   271.2 2007.99
   351.1    1996   384.4 1994.48   397.2 1992.87     421 1988.53   470.8  1982.3
   536.8 1977.31  541.741976.377   546.7 1975.39  558.011976.378   570.1 1978.68
     583 1979.52   606.1 1979.75   655.6 1983.59   685.3 1984.89   711.7 1988.11
   731.6 1991.94     771 2001.89   780.9 2003.72   794.2  2007.2   830.4 2015.18
   853.5 2018.44   869.9 2022.25   902.9 2026.52   939.2 2028.72962.8135 2031.26
#Mann= 3 ,-1 , 0
       0     .05       0  541.74    .045       0  558.01     .05       0
Bank Sta=541.74,558.01
XS Rating Curve= 0 ,0
Exp/Cntr(USF)=0,0
Exp/Cntr=0.3,0.1

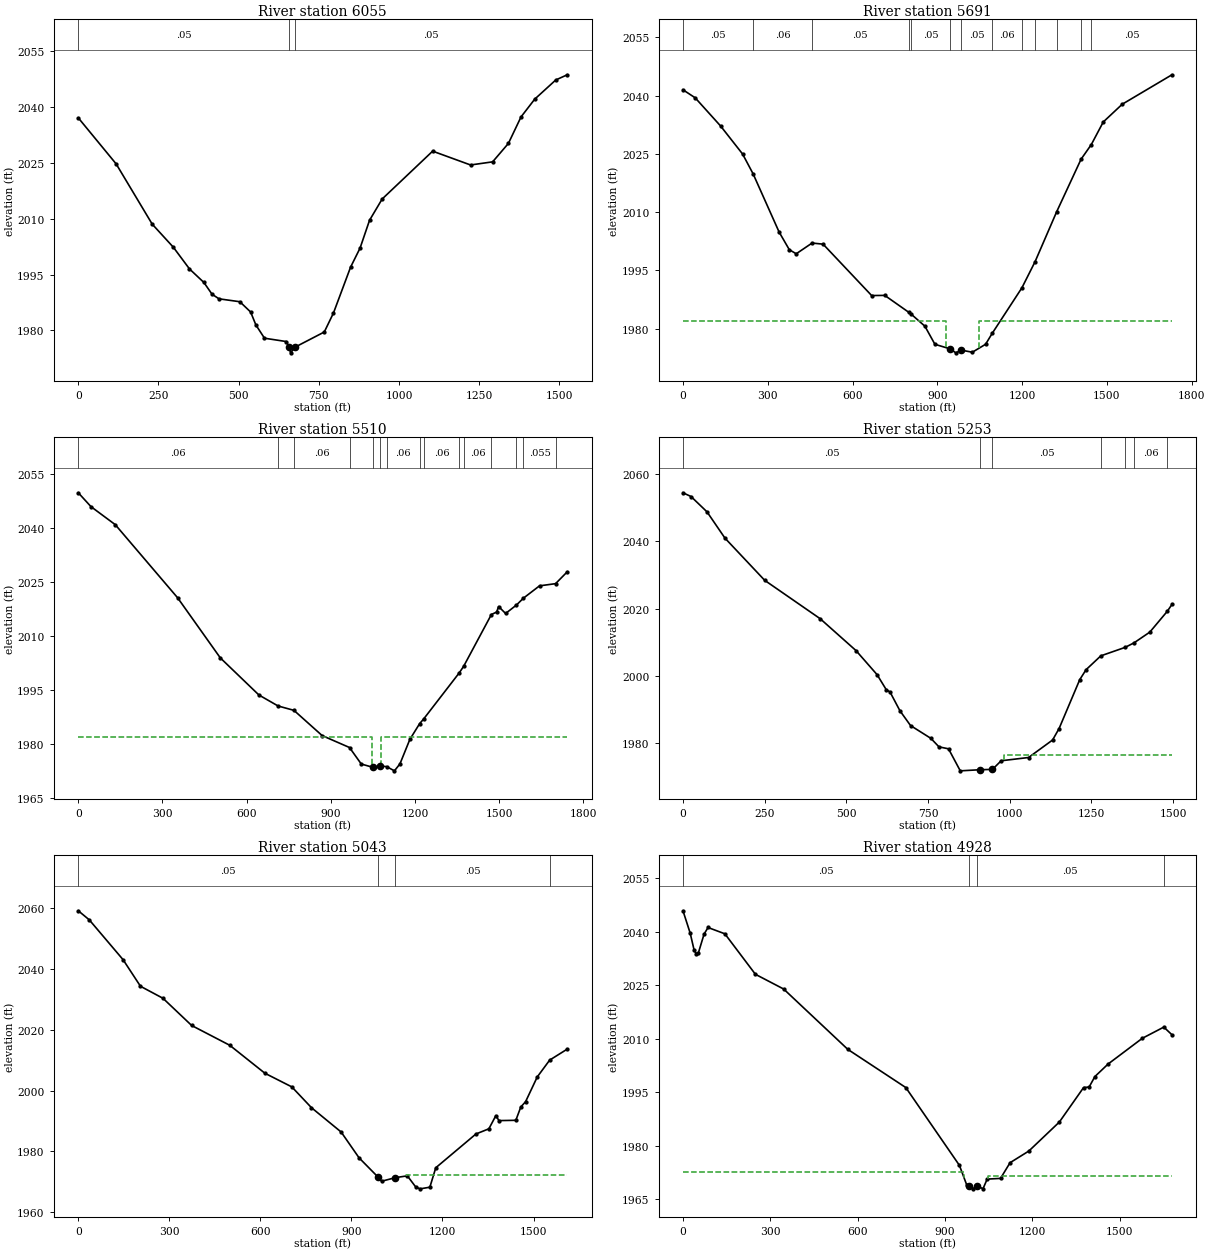
Type RM Length L Ch R = 1 ,6055    ,364.1,364.1,364.1
XS GIS Cut Line= 4
2120022.49084339312576.5720957252119764.10162409313044.133540185
2119770.25374836313323.0298403892119770.25374836314034.625547528
#Sta/Elev= 30
       0 2037.11     118 2024.75   230.5 2008.56   296.4 2002.36   346.7 1996.53
   391.7 1992.89   417.1 1989.73   438.8  1988.5   503.8 1987.72   537.4 1984.96
   553.8 1981.48   580.6 1977.92     649 1977.02  656.881975.555   662.1 1973.99
  676.771975.556   767.1 1979.59   795.8 1984.71   849.1 1997.01   878.7 2002.14
   908.2  2009.6   947.6 2015.32    1105 2028.17  1223.2 2024.46  1292.1  2025.3
  1341.3 2030.26  1380.6 2037.37  1423.3 2042.14  1488.9 2047.291524.768 2048.69
#Mann= 3 ,-1 , 0
       0     .05       0  656.88    .045       0  676.77     .05       0
Bank Sta=656.88,676.77
XS Rating Curve= 0 ,0
Exp/Cntr(USF)=0,0
Exp/Cntr=0.5,0.3

Type RM Length L Ch R = 1 ,5691    ,181.3,181.3,181.3
XS GIS Cut Line= 4
2119995.83163823312508.8987287642119530.32090186313195.885938826
2119325.25009288313513.7456927352119077.11441402313973.104304836
#Sta/Elev= 30
       0 2041.51    43.1 2039.45   132.9  2032.2   210.9 2024.97  248.162019.854
   340.1 2004.87   376.2 2000.32   400.7 1999.26  456.842002.028   495.8 2001.74
   667.6  1988.5     714 1988.54   798.31984.221  807.251983.728   856.1  1980.6
   891.5 1975.94   945.9 1974.75   965.4 1973.74   984.9 1974.43    1024  1973.9
  1070.8 1975.95 1094.161978.754 1199.451990.505 1245.831997.213 1322.472010.111
 1408.662023.625 1444.952027.402  1487.2 2033.22  1554.3 2037.791730.215 2045.38
#Mann= 13 ,-1 , 0
       0     .05       0  248.16     .06       0  456.84     .05       0
   798.3    .055       0  807.25     .05       0   945.9    .045       0
   984.9     .05       0 1094.16     .06       0 1199.45     .05       0
 1245.83    .055       0 1322.47     .05       0 1408.66    .055       0
 1444.95     .05       0
#XS Ineff= 2 , 0
           931.2 1982.05 1047.27            1982
Permanent Ineff=
       F       F
Bank Sta=945.9,984.9
XS Rating Curve= 0 ,0
Exp/Cntr(USF)=0,0
Exp/Cntr=0.5,0.3

Type RM Length L Ch R = 1 ,5510    ,256.2,256.2,256.2
XS GIS Cut Line= 4
2119835.87640723312478.1381074182119353.96000614313286.117094774
2119140.68636481313608.0782648632118980.73113381313991.560677644
#Sta/Elev= 30
       0 2049.88    45.2 2046.02   131.7 2041.01   353.9 2020.66   506.1 2003.93
   643.6 1993.61  712.071990.544  768.431989.335     869 1982.31  966.48 1978.99
  1008.5 1974.39 1048.591973.511  1075.4 1973.82 1098.49 1973.68  1126.6  1972.5
  1146.3 1974.44  1181.7 1981.27 1216.531985.644  1230.5 1986.91 1357.761999.785
 1373.162001.575 1472.132016.004  1490.8 2016.69  1497.9 2018.22  1522.8 2016.29
 1561.352018.635  1586.52020.564  1643.6 2023.98 1700.872024.5911742.481 2027.89
#Mann= 15 ,-1 , 0
       0     .06       0  712.07    .055       0  768.43     .06       0
  966.48    .055       0 1048.59    .045       0  1075.4     .05       0
 1098.49     .06       0 1216.53     .05       0  1230.5     .06       0
 1357.76    .055       0 1373.16     .06       0 1472.13    .055       0
 1561.35     .06       0  1586.5    .055       0 1700.87     .05       0
#XS Ineff= 2 , 0
            1045    1982    1078            1982
Permanent Ineff=
       F       F
Bank Sta=1048.59,1075.4
XS Rating Curve= 0 ,0
Exp/Cntr(USF)=0,0
Exp/Cntr=0.5,0.3

Type RM Length L Ch R = 1 ,5253    ,210.1,210.1,210.1
XS GIS Cut Line= 4
2119429.83620546312578.6228038152119116.07786773313296.370635223
 2118982.7818419313589.6218920552118933.56484774313977.205721016
#Sta/Elev= 30
       0 2054.38    24.6 2053.27    73.5 2048.72   128.4 2040.92   250.1 2028.38
   419.8 2016.99   529.4 2007.53   593.9 2000.38   622.5 1995.84   633.3 1995.27
   663.9 1989.65   696.3 1985.27   758.6 1981.46   783.3 1978.94   812.5 1978.36
   848.5 1971.82   909.5 1972.15  946.95 1972.25   973.6 1974.81  1057.5 1975.78
  1130.9 1980.97  1150.8 1984.37  1214.2 1998.92  1233.5 2001.86 1278.55 2005.96
 1353.042008.483 1380.042009.815  1428.5 2013.01 1481.542019.1441496.151 2021.21
#Mann= 7 ,-1 , 0
       0     .05       0   909.5    .045       0  946.95     .05       0
 1278.55     .06       0 1353.04     .05       0 1380.04     .06       0
 1481.54    .055       0
#XS Ineff= 2 , 0
                          982.16         1976.44
Permanent Ineff=
       F       F
Bank Sta=909.5,946.95
XS Rating Curve= 0 ,0
Exp/Cntr(USF)=0,0
Exp/Cntr=0.5,0.3

Type RM Length L Ch R = 1 ,5043    ,114.9,114.9,114.9
XS GIS Cut Line= 4
2119290.38805536312525.3043934812118935.61555583313327.131256569
2118810.52236236313640.8895942992118835.13085943314036.676255618
#Sta/Elev= 30
       0 2059.24    36.3 2056.24   147.5 2043.14   204.9 2034.38   279.1 2030.42
   373.5 2021.47   499.1 2014.95   614.9 2005.74   703.6 2001.25   768.2 1994.41
   866.1 1986.39   925.2 1977.88   988.8 1971.44   999.4 1970.18    1045 1971.37
  1084.2 1971.96  1112.4 1968.22  1126.6 1967.68  1158.4 1968.22  1177.9 1974.62
  1310.2 1985.74  1352.9 1987.45  1375.9 1991.79  1386.1 1990.15  1441.7 1990.25
  1458.1 1994.64  1473.8 1996.37  1512.3 2004.53 1553.252010.0741611.134 2013.69
#Mann= 4 ,-1 , 0
       0     .05       0   988.8    .045       0    1045     .05       0
 1553.25     .06       0
#XS Ineff= 2 , 0
          967.07  1972.7 1079.38         1972.18
Permanent Ineff=
       F       F
Bank Sta=988.8,1045
XS Rating Curve= 0 ,0
Exp/Cntr(USF)=0,0
Exp/Cntr=0.5,0.3

Type RM Length L Ch R = 1 ,4928    ,277.3,277.3,277.3
XS GIS Cut Line= 4
 2119062.7594574312515.0508530332118816.67448663313390.703207351
 2118722.3419145 313628.58534576 2118761.3053682314141.262368195
#Sta/Elev= 30
       0 2045.91    24.7 2039.65    38.3 2034.86    45.1 2033.88    53.2 2034.17
    72.4 2039.35      86 2041.22   143.9 2039.45   248.8 2028.09   345.8 2023.96
   566.5 2007.01   765.5 1996.31   949.6 1974.49   974.3 1969.08     983 1968.75
   995.7  1967.9  1009.6 1968.67  1030.8 1967.95  1044.9 1970.63  1090.8 1970.83
  1123.6 1975.23    1188  1978.5    1293 1986.65    1376  1996.3  1395.2 1996.47
    1415  1999.4  1460.4 2002.92  1577.8 2010.13 1651.732013.2751679.633 2011.13
#Mann= 4 ,-1 , 0
       0     .05       0     983    .045       0  1009.6     .05       0
 1651.73     .06       0
#XS Ineff= 2 , 0
          965.51  1972.7 1048.43         1971.59
Permanent Ineff=
       F       F
Bank Sta=983,1009.6
XS Rating Curve= 0 ,0
Exp/Cntr(USF)=0,0
Exp/Cntr=0.5,0.3