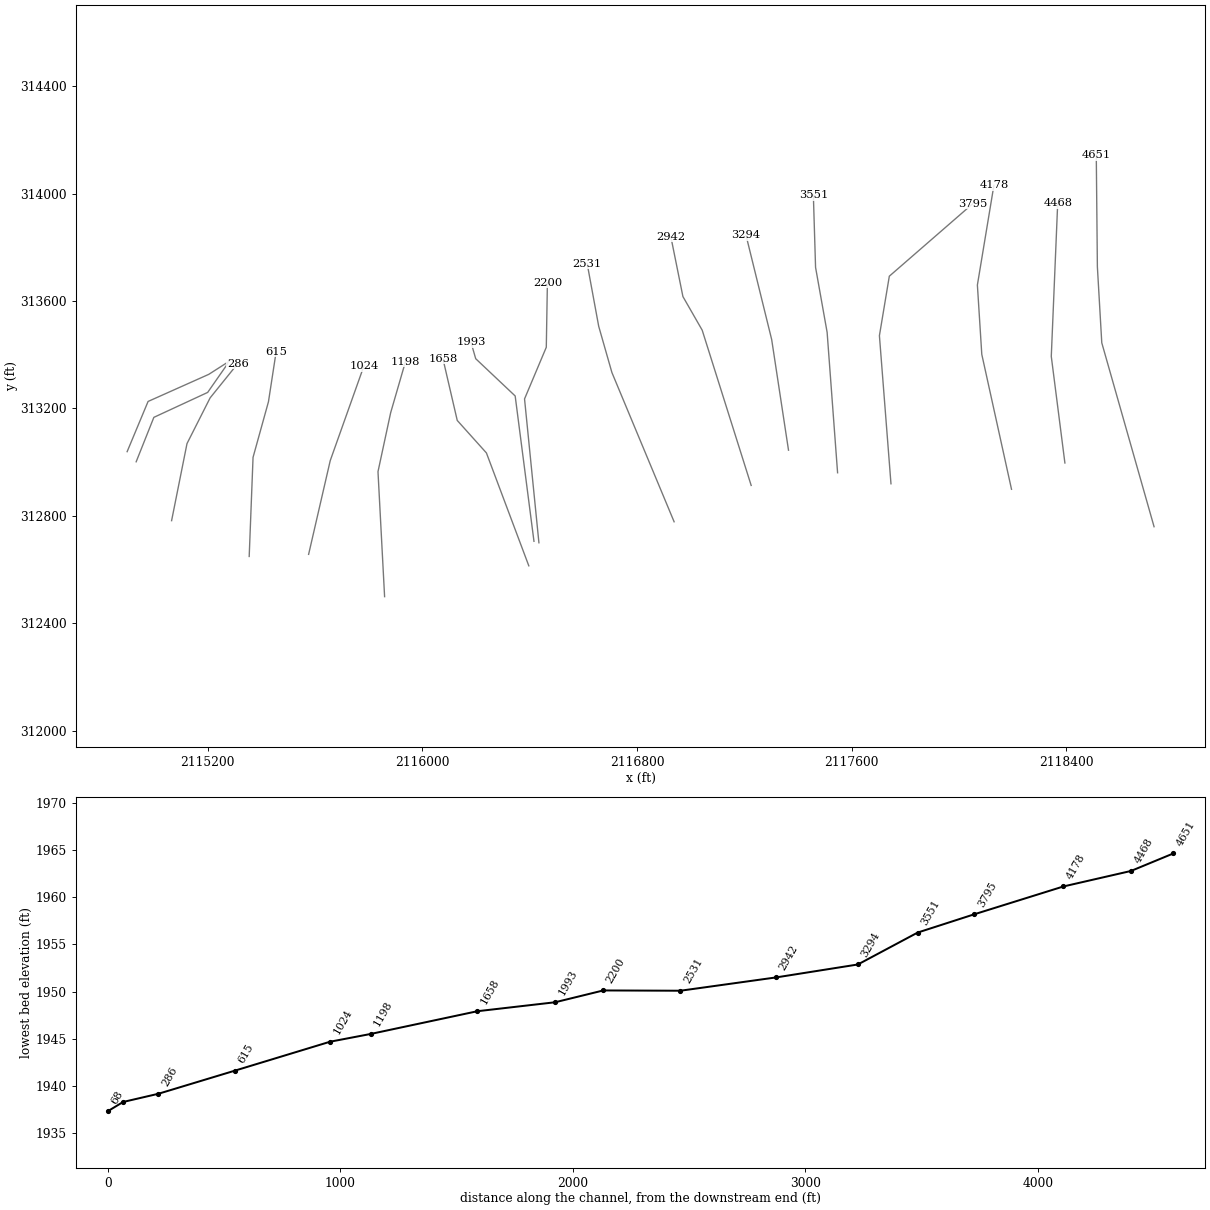
HEC-RAS study MLGNCKTR3.prj: MLGNCKTR3

--- MLGNCKTR3.g01 (geometry) --- (continued)

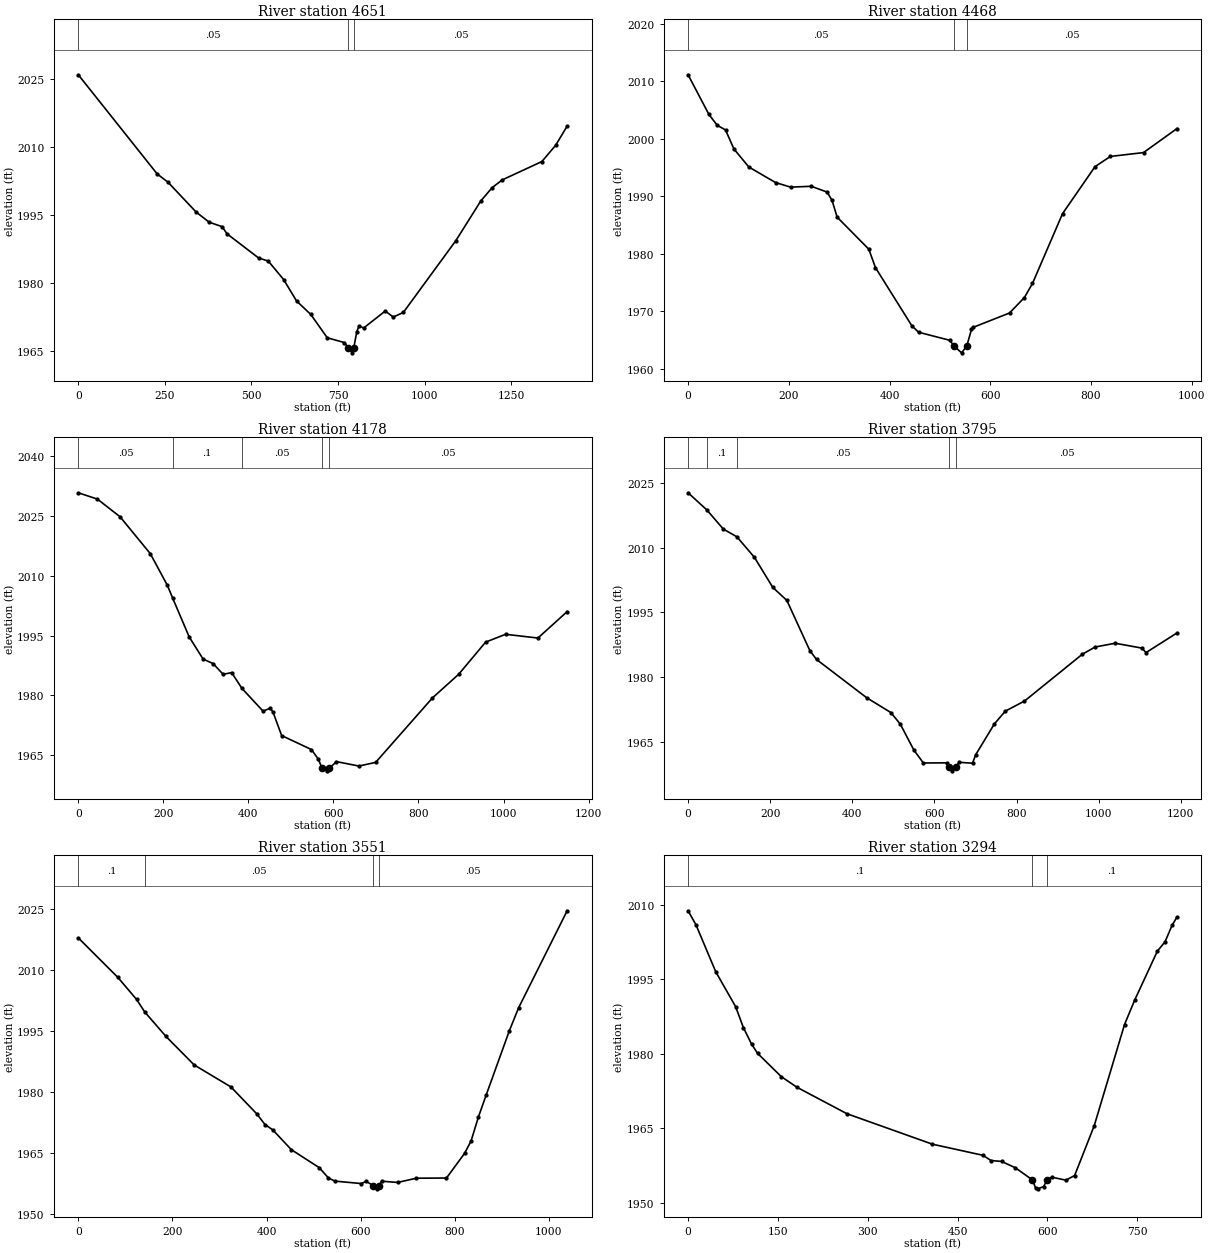
Type RM Length L Ch R = 1 ,4651    ,182.8,182.8,182.8
XS GIS Cut Line= 4
2118726.44333068312759.0851157122118531.62606215313444.021617684
2118515.22039744313727.0193340682118511.11898126314143.313076284
#Sta/Elev= 30
       0    2026     228  2004.1   258.7 2002.32   340.2 1995.71   378.1 1993.46
   415.6 1992.47   429.3 1990.91   520.7 1985.57   548.7 1984.88     593 1980.81
   630.5 1976.06   671.5  1973.1     719 1967.96   767.8 1966.91   780.21965.754
   791.3 1964.63  795.611965.755   804.4  1969.3     811 1970.58   824.1 1970.11
   886.6 1973.86   909.6 1972.53   938.7 1973.54  1090.2 1989.37  1162.3 1998.13
  1195.2 2001.09  1224.7 2002.81  1338.9 2006.85  1378.9 2010.461411.891 2014.68
#Mann= 3 ,-1 , 0
       0     .05       0   780.2    .045       0  795.61     .05       0
Bank Sta=780.2,795.61
XS Rating Curve= 0 ,0
Exp/Cntr(USF)=0,0
Exp/Cntr=0.3,0.1

Type RM Length L Ch R = 1 ,4468    ,290.4,290.4,290.4
XS GIS Cut Line= 3
2118394.22762044 312996.447028572118343.48391515313393.441899359
2118367.36330587313963.562352897
#Sta/Elev= 30
       0 2011.09    41.4 2004.19    57.9 2002.31    74.4  2001.5      91  1998.2
   120.7 1995.06   173.7 1992.36   203.4 1991.57   244.8 1991.71   276.2  1990.7
   285.9 1989.26     296 1986.35   358.9 1980.78   372.1 1977.58   444.3 1967.48
   457.7 1966.35   520.1 1964.94   527.1 1964.04   543.1 1962.77   553.41963.952
   562.8 1966.83   566.1  1967.2   638.3 1969.69   667.9 1972.38   683.9 1974.82
   743.7 1986.97   808.1 1995.12   838.6  1996.9   904.5 1997.57   970.8 2001.74
#Mann= 3 , 0 , 0
       0     .05       0   527.1    .045       0   553.4     .05       0
Bank Sta=527.1,553.4
XS Rating Curve= 0 ,0
Exp/Cntr(USF)=0,0
Exp/Cntr=0.3,0.1

Type RM Length L Ch R = 1 ,4178    ,382.5,382.5,382.5
XS GIS Cut Line= 4
2118195.30993544312898.5332658142118084.57169859313400.956747799
2118068.16603387313659.3459671062118129.68727657314030.524131349
#Sta/Elev= 30
       0 2030.77    44.9 2029.19    98.3 2024.75   169.2 2015.54   209.5 2007.59
  221.792004.426   260.7 1994.69   293.5 1989.12     317    1988   340.5 1985.31
   360.7 1985.73  384.831981.778   434.6 1976.07   451.4 1976.83   458.1 1975.79
   478.2 1969.97   548.1 1966.47   564.5 1964.06  573.181961.807   584.2 1961.13
  590.541961.808   607.2 1963.44   659.8 1962.33   699.3 1963.25   832.9  1979.4
   894.6 1985.32   957.8 1993.36  1004.8 1995.33  1080.9 1994.391149.634 2001.01
#Mann= 5 ,-1 , 0
       0     .05       0  221.79      .1       0  384.83     .05       0
  573.18    .045       0  590.54     .05       0
Bank Sta=573.18,590.54
XS Rating Curve= 0 ,0
Exp/Cntr(USF)=0,0
Exp/Cntr=0.3,0.1

Type RM Length L Ch R = 1 ,3795    ,244.2,244.2,244.2
XS GIS Cut Line= 4
2117746.20486378312919.040346711 2117703.1399939313470.680822851
2117740.05273952313692.1572965422118051.76036916313962.850764387
#Sta/Elev= 30
       0 2022.74   45.39 2018.79    85.9 2014.31  118.92 2012.52   161.6 2007.75
   206.2 2000.79   240.6 1997.75   296.5 1986.12   312.8 1984.05   434.7 1975.18
     494 1971.72     517 1969.01   549.9 1963.02   573.1 1960.01   629.7 1960.05
  635.051959.122   643.5 1958.19  652.891959.123   659.6 1960.18   692.9 1959.96
   700.5 1961.92   746.1  1969.1   772.7 1972.05   819.4 1974.39   960.3 1985.26
   991.5 1986.94  1040.3 1987.81  1105.5 1986.68  1115.4 1985.64 1190.69 1990.19
#Mann= 5 ,-1 , 0
       0     .05       0   45.39      .1       0  118.92     .05       0
  635.05    .045       0  652.89     .05       0
Bank Sta=635.05,652.89
XS Rating Curve= 0 ,0
Exp/Cntr(USF)=0,0
Exp/Cntr=0.3,0.1

Type RM Length L Ch R = 1 ,3551    ,257.2,257.2,257.2
XS GIS Cut Line= 4
2117547.28617908312960.0545085062117508.32272538313482.985071389
2117465.25785549313724.9686259782117457.05502313313993.611385734
#Sta/Elev= 30
       0 2017.97    84.2 2008.24   123.7 2002.85  141.161999.758   186.2 1993.75
   246.2 1986.73   324.4 1981.31   379.6 1974.66   396.8 1972.05   413.2 1970.77
   452.7 1965.89   511.9 1961.47   531.7 1958.92   545.1 1958.15   601.7 1957.55
   611.7 1958.09  626.72 1957.06   634.9 1956.25  638.741957.059     645 1958.13
   678.4 1957.82   718.4 1958.86   782.5 1958.91   820.9 1964.97   834.7 1968.01
   850.4 1973.94   866.8 1979.31   916.1 1995.14   935.8 2000.791038.934 2024.64
#Mann= 4 ,-1 , 0
       0      .1       0  141.16     .05       0  626.72    .045       0
  638.74     .05       0
Bank Sta=626.72,638.74
XS Rating Curve= 0 ,0
Exp/Cntr(USF)=0,0
Exp/Cntr=0.3,0.1

Type RM Length L Ch R = 1 ,3294    ,351.5,351.5,351.5
XS GIS Cut Line= 3
2117364.42889546313044.2058100182117301.74549481 313456.12530001
2117206.22793191313844.165399277
#Sta/Elev= 30
       0 2008.74    13.1 2005.94    46.3 1996.46    79.5 1989.45    92.3 1985.28
     106 1981.95     116  1980.1   155.7 1975.41   181.6 1973.29   265.3 1967.96
     408 1961.84   492.3 1959.61   505.8 1958.56   523.4 1958.38   546.4 1957.11
     575 1954.66   580.2 1953.08   583.6 1952.87   593.7 1953.32   599.4 1954.69
   607.2 1955.22   630.9 1954.61   645.5 1955.55   678.2 1965.56   728.8 1985.89
   745.7 1990.78   783.7 2000.65   796.4  2002.5   808.1 2005.79   816.3 2007.47
#Mann= 3 , 0 , 0
       0      .1       0     575    .045       0   599.4      .1       0
Bank Sta=575,599.4
XS Rating Curve= 0 ,0
Exp/Cntr(USF)=0,0
Exp/Cntr=0.3,0.1

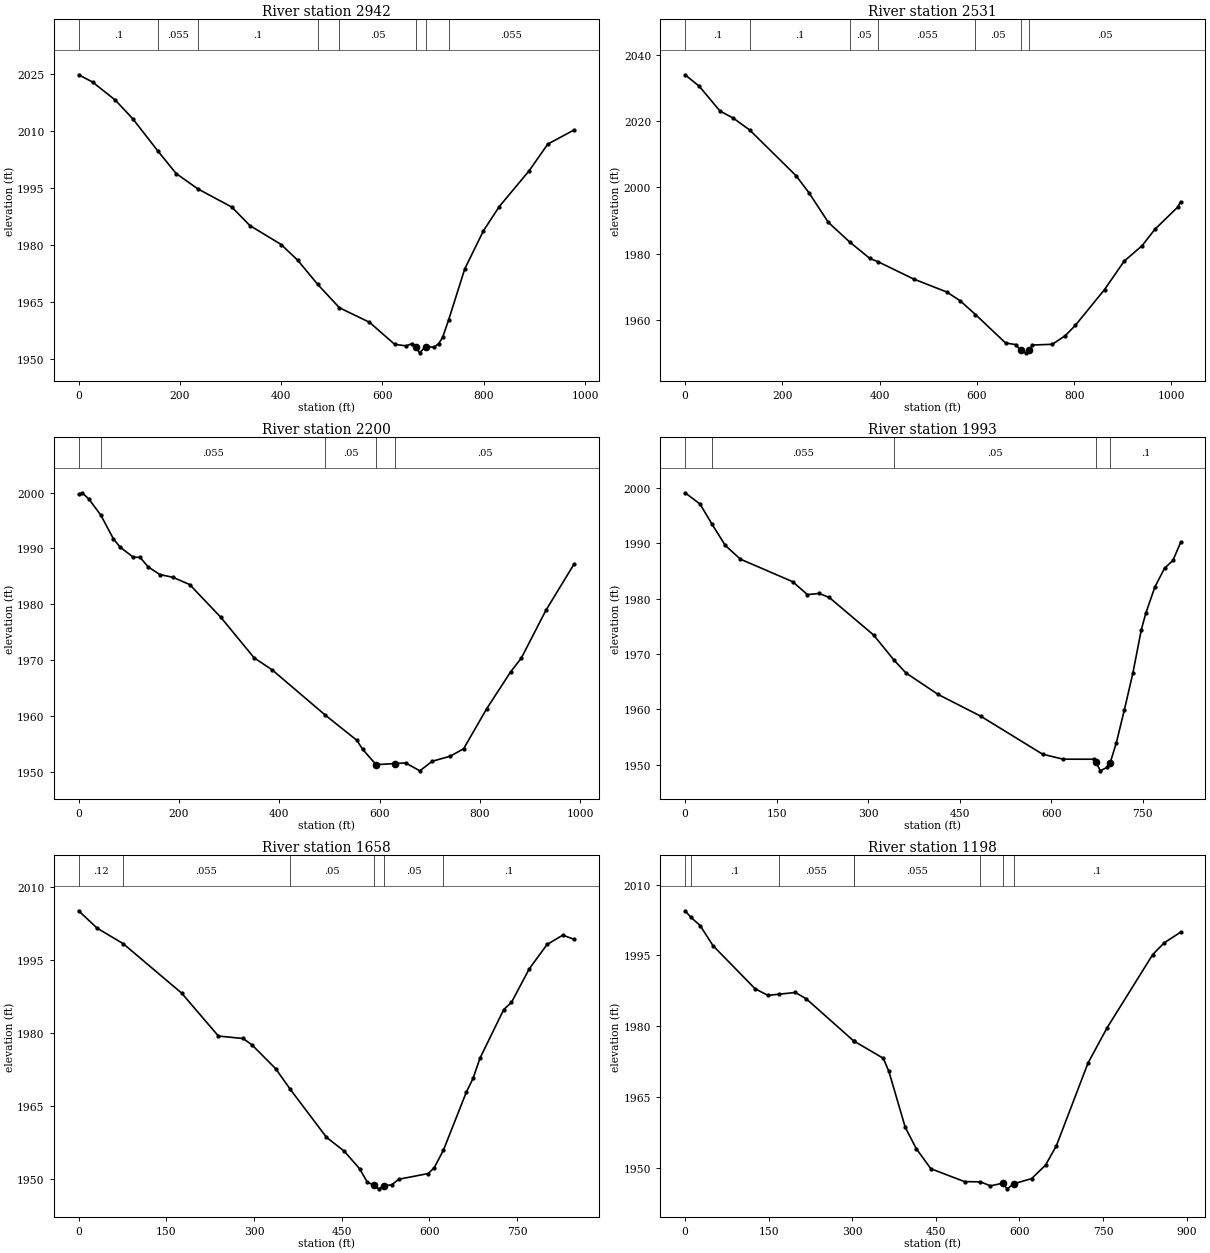
Type RM Length L Ch R = 1 ,2942    ,411.7,411.7,411.7
XS GIS Cut Line= 4
2117225.32500899312912.888222442  2117042.811989313491.187903748
2116971.03720586313616.2810972222116925.92162789313839.808279003
#Sta/Elev= 30
       0 2024.91    27.4    2023    72.2 2018.25   106.6 2013.35  157.212004.665
   192.6 1998.84  235.631994.771   302.5 1989.98   338.2 1985.11     400  1980.1
   432.7 1975.94  472.151969.576  515.061963.398   574.4 1959.57   624.2 1953.74
   646.7 1953.34   658.7 1953.94  665.641953.122   673.4  1951.5   685.2 1953.16
     702 1952.98   711.2 1953.96   718.8 1955.56  730.951960.286   762.6 1973.67
   799.4  1983.7   830.7 1990.11   889.8 1999.58   926.6 2006.62978.6735 2010.36
#Mann= 8 ,-1 , 0
       0      .1       0  157.21    .055       0  235.63      .1       0
  472.15    .055       0  515.06     .05       0  665.64    .045       0
   685.2     .05       0  730.95    .055       0
Bank Sta=665.64,685.2
XS Rating Curve= 0 ,0
Exp/Cntr(USF)=0,0
Exp/Cntr=0.3,0.1

Type RM Length L Ch R = 1 ,2531    ,331.6,331.6,331.6
XS GIS Cut Line= 4
2116938.22587643312777.5414885192116706.49586229313333.283380838
2116657.27886813313505.5428603762116614.21399825313739.323582606
#Sta/Elev= 30
       0 2033.94    29.3 2030.45    71.9 2022.98    98.9 2020.89  132.962017.273
   228.3 2003.48   254.4 1998.43   294.5 1989.44  338.571983.499   379.8 1978.56
  396.421977.583     470 1972.35   537.9 1968.44   565.5 1965.81  597.041961.647
   658.9 1953.08   680.1 1952.56  690.221950.798   700.5 1950.09  707.471950.798
   714.2 1952.44   755.1 1952.67   781.3 1955.21   802.4 1958.36   862.5 1969.17
   902.5 1977.67   939.9 1982.43   965.9 1987.32  1012.6 1993.981018.986 1995.65
#Mann= 7 ,-1 , 0
       0      .1       0  132.96      .1       0  338.57     .05       0
  396.42    .055       0  597.04     .05       0  690.22    .045       0
  707.47     .05       0
Bank Sta=690.22,707.47
XS Rating Curve= 0 ,0
Exp/Cntr(USF)=0,0
Exp/Cntr=0.3,0.1

Type RM Length L Ch R = 1 ,2200    ,206.9,206.9,206.9
XS GIS Cut Line= 4
2116434.52441805312699.3149881712116380.94530368313235.106131845
2116462.00088696313427.4414141892116466.12235729 313667.86051712
#Sta/Elev= 30
       01999.664   6.8341999.958  20.1681998.859  44.1471995.963   69.481991.677
  83.1141990.186 109.0471988.402 122.2351988.393 138.7211986.675 161.8021985.304
 188.1791984.803  221.341983.507  283.621977.612 349.7421970.378 386.0111968.198
 491.5221960.109 554.5891955.586 566.1021953.975   592.81951.226   629.81951.423
 651.5491951.545 680.031 1950.12 704.6811951.834 740.5561952.742 767.3251954.079
 813.264 1961.25 861.2581967.894 882.1711970.311 931.3911978.906 987.6351987.209
#Mann= 5 ,-1 , 0
       0     .12       0  44.147    .055       0 491.522     .05       0
   592.8    .045       0   629.8     .05       0
Bank Sta=592.8,629.8
XS Rating Curve= 0 ,0
Exp/Cntr(USF)=0,0
Exp/Cntr=0.3,0.1

Type RM Length L Ch R = 1 ,1993    ,334.7,334.7,334.7
XS GIS Cut Line= 4
2116416.09615411312704.810281953 2116346.0311584313246.096719408
2116199.03204975313384.8528873852116181.17234496313446.674942424
#Sta/Elev= 30
       0 1999.15    24.5 1997.11    44.3 1993.45    65.7 1989.65    90.6 1987.15
   176.2 1983.08   200.5 1980.74   219.7 1980.94   236.2 1980.23     309 1973.43
   342.1 1968.94   361.9 1966.58   414.8 1962.68   484.6 1958.75     586 1951.88
   619.5 1950.98   670.7 1950.97   673.11950.556   680.6 1948.87   692.2 1949.53
   696.9 1950.37   706.8  1953.9   720.1 1959.92   733.9 1966.49   747.9 1974.41
   755.2 1977.37   770.1 1982.12   785.9  1985.5   799.6 1986.91   812.3 1990.17
#Mann= 5 ,-1 , 0
       0     .12       0    44.3    .055       0   342.1     .05       0
   673.1    .045       0   696.9      .1       0
Bank Sta=673.1,696.9
XS Rating Curve= 0 ,0
Exp/Cntr(USF)=0,0
Exp/Cntr=0.3,0.1

Type RM Length L Ch R = 1 ,1658    ,459.4,459.4,459.4
XS GIS Cut Line= 4
2116396.83894074 312613.484841342116238.93441783313033.879999736
2116130.24688907313154.8717770312116076.92847874313384.551083081
#Sta/Elev= 30
       0 2005.07    31.6  2001.5   76.141998.315   176.1 1988.16   239.1 1979.32
   281.2 1978.82   296.6  1977.5   337.3 1972.57  361.181968.499   423.9 1958.51
   454.2 1955.67   480.4 1952.07   493.5 1949.35   505.1 1948.62   513.1 1947.92
   522.9  1948.6   535.3 1948.73   547.5 1949.89   598.1 1951.07   608.3  1952.3
  623.921955.878     663 1967.77   674.5  1970.6   686.5  1974.8     727 1984.76
   740.3 1986.25   770.7 1993.14   801.1 1998.14     828 2000.06847.4998  1999.2
#Mann= 6 ,-1 , 0
       0     .12       0   76.14    .055       0  361.18     .05       0
   505.1    .045       0   522.9     .05       0  623.92      .1       0
Bank Sta=505.1,522.9
XS Rating Curve= 0 ,0
Exp/Cntr(USF)=0,0
Exp/Cntr=0.3,0.1

Type RM Length L Ch R = 1 ,1198    ,174.2,174.2,174.2
XS GIS Cut Line= 4
2115859.55342123312498.6451883152115834.94492415312964.155924685
2115882.11121021313183.5816902872115937.48032864313374.297542633
#Sta/Elev= 30
       0 2004.46   10.132003.109    27.1 2001.31    50.1 1997.06   125.6 1987.93
   148.6 1986.53  168.611986.774   197.9 1987.14   217.6 1985.78  302.31 1976.88
  302.521976.866   355.6 1973.19   365.5 1970.47     395 1958.56   414.7 1954.05
     441 1949.77   501.4 1947.04  529.911946.991   547.9 1946.14   569.6  1946.7
   577.9 1945.51  589.731946.587   621.7 1947.67   646.8 1950.54   666.3 1954.66
   722.9 1972.16   757.1 1979.63   839.1 1995.18   859.6 1997.66889.1893 1999.93
#Mann= 8 ,-1 , 0
       0      .1       0   10.13      .1       0  168.61    .055       0
  302.31      .1       0  302.52    .055       0  529.91      .1       0
   569.6    .045       0  589.73      .1       0
Bank Sta=569.6,589.73
XS Rating Curve= 0 ,0
Exp/Cntr(USF)=0,0
Exp/Cntr=0.3,0.1

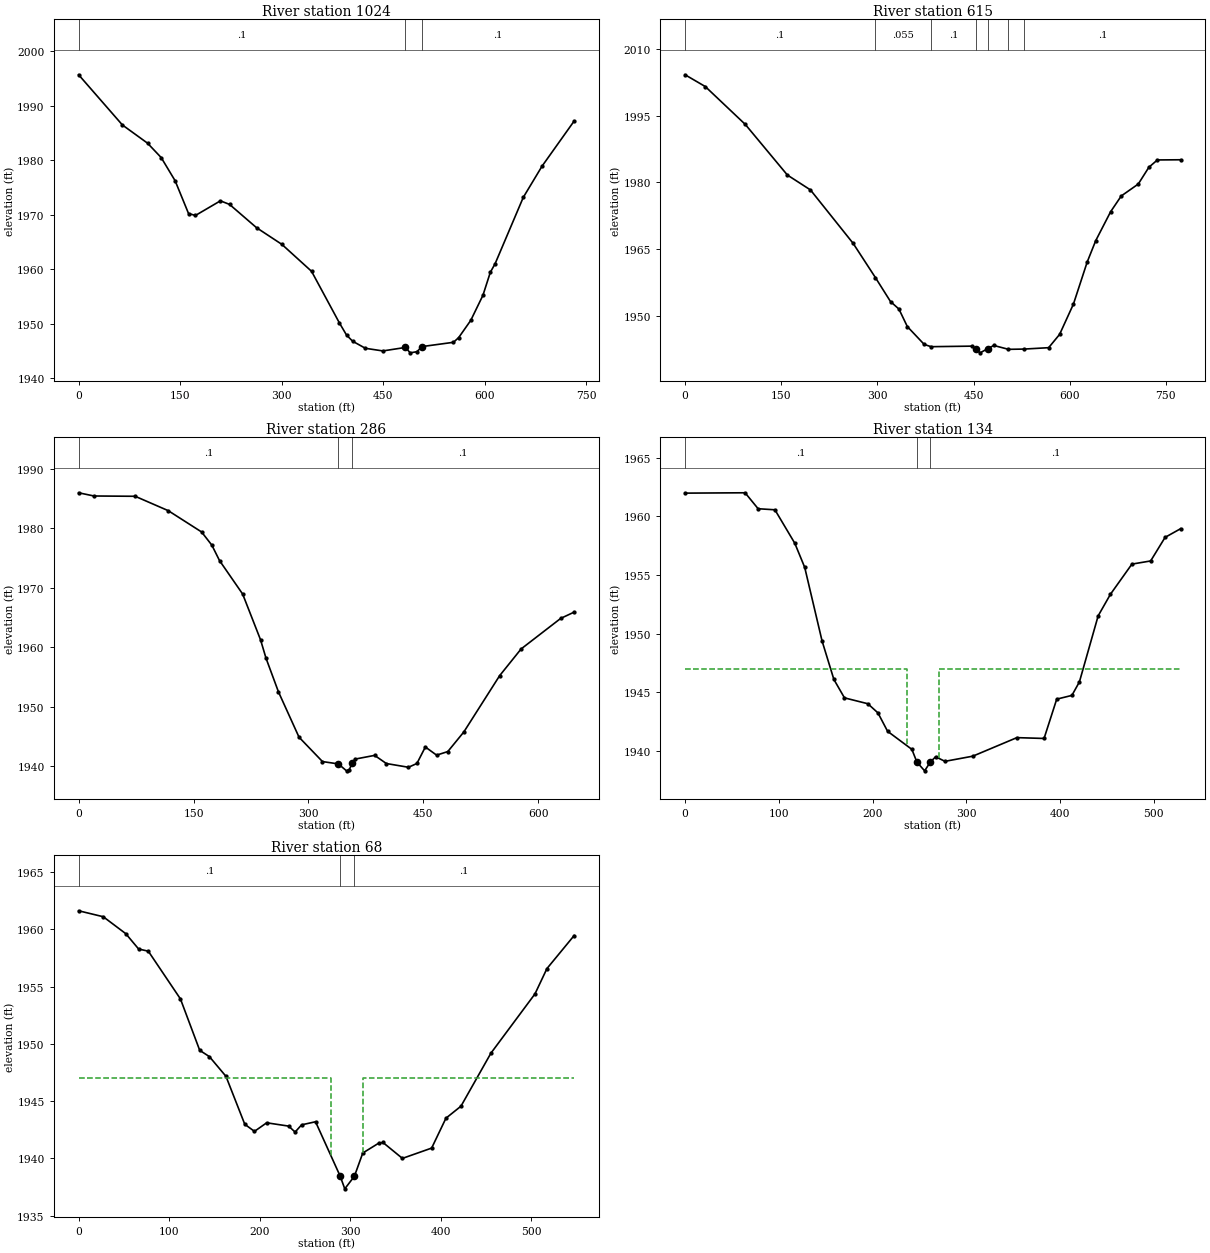
Type RM Length L Ch R = 1 ,1024    ,408.9,408.9,408.9
XS GIS Cut Line= 3
2115576.45951499312656.1657107512115657.05245868313005.401800092
2115782.41925999313357.622813272
#Sta/Elev= 30
       0 1995.64    64.7 1986.44   101.8 1983.11     122 1980.47   142.6 1976.22
   162.4 1970.22   172.6 1969.86   209.5 1972.54     223 1971.89   262.9 1967.62
   300.4 1964.56   344.2 1959.63   385.5 1950.14   395.9 1947.95   404.9 1946.82
   423.8 1945.52   449.6 1945.04     483 1945.68     490 1944.69   499.9  1944.9
   507.6 1945.84   553.9 1946.62   561.6 1947.48   579.5 1950.64   597.5 1955.24
   608.4 1959.45   615.5 1961.03   657.1 1973.18   684.8 1978.89   732.3 1987.17
#Mann= 3 , 0 , 0
       0      .1       0     483    .045       0   507.6      .1       0
Bank Sta=483,507.6
XS Rating Curve= 0 ,0
Exp/Cntr(USF)=0,0
Exp/Cntr=0.3,0.1

Type RM Length L Ch R = 1 ,615     ,329.2,329.2,329.2
XS GIS Cut Line= 4
2115355.07923115312648.3468788662115369.43418778313017.474335018
2115426.85401429313224.5958520822115455.56392755313411.210288248
#Sta/Elev= 30
       0 2004.22    31.5 2001.57    93.9 1993.05   159.6 1981.65   195.6  1978.3
   262.2 1966.27  296.991958.556   320.5 1953.17   333.6 1951.49   346.7 1947.55
   373.1 1943.52  383.781943.014     448 1943.14  453.581942.484   460.3 1941.63
   471.9 1942.55   481.6 1943.29  504.56 1942.42  528.961942.478   567.2 1942.79
   584.3 1945.78   605.9 1952.61   627.4 1962.09   640.7 1966.89   663.9 1973.39
   680.5 1976.94     707 1979.62   723.6  1983.4   736.9 1985.05773.1498 1985.09
#Mann= 7 ,-1 , 0
       0      .1       0  296.99    .055       0  383.78      .1       0
  453.58    .045       0   471.9      .1       0  504.56     .05       0
  528.96      .1       0
Bank Sta=453.58,471.9
XS Rating Curve= 0 ,0
Exp/Cntr(USF)=0,0
Exp/Cntr=0.3,0.1

Type RM Length L Ch R = 1 ,286     ,151.9,151.9,151.9
XS GIS Cut Line= 4
 2115065.9293905312781.6429046992115123.34921701313068.742037262
2115209.47895678 313238.950808712115312.01436127313366.094710274
#Sta/Elev= 30
       0 1985.95      20 1985.41    73.8 1985.36     117 1982.94   160.5 1979.36
   173.9 1977.14   183.9 1974.55   214.1 1968.92   237.5 1961.21   244.6 1958.13
   260.9 1952.45   287.7 1944.84   318.3 1940.74  339.081940.345   349.7 1939.18
   353.3 1939.39     357 1940.43   360.7 1941.15   386.4 1941.78   401.7 1940.41
   430.6 1939.78   441.6 1940.42   452.6 1943.19   467.3 1941.82   481.9 1942.42
   502.9 1945.73   549.6 1955.19   577.6 1959.68   629.3 1964.82646.8821 1965.88
#Mann= 3 ,-1 , 0
       0      .1       0  339.08    .045       0     357      .1       0
Bank Sta=339.08,357
XS Rating Curve= 0 ,0
Exp/Cntr(USF)=0,0
Exp/Cntr=0.5,0.3

Type RM Length L Ch R = 1 ,134     ,65.9,65.9,65.9
XS GIS Cut Line= 4
2114933.95320039 313000.95444586 2114999.8812097313166.447203914
2115200.35617677313259.2846047742115274.35700354 313365.57670141
#Sta/Elev= 30
       0 1961.98      64 1962.01    77.9 1960.65    95.8 1960.56     117 1957.71
   127.6 1955.65   146.1 1949.38   158.7  1946.1     170 1944.53   194.9 1944.03
   205.7 1943.25     216 1941.68   241.9 1940.14  247.281939.052   255.5 1938.31
  261.521939.051   267.2 1939.51   277.2 1939.12   306.9 1939.56   353.9 1941.14
   382.9 1941.07   396.4 1944.42   412.6 1944.74   420.6 1945.89   440.6 1951.52
   453.7 1953.36   476.6 1955.93   496.6  1956.2     512 1958.21 528.584 1958.95
#Mann= 3 ,-1 , 0
       0      .1       0  247.28    .045       0  261.52      .1       0
#XS Ineff= 2 , 0
             237    1947     271            1947
Permanent Ineff=
       F       F
Bank Sta=247.28,261.52
XS Rating Curve= 0 ,0
Exp/Cntr(USF)=0,0
Exp/Cntr=0.5,0.3

Type RM Length L Ch R = 1 ,68      ,26.1,26.1,26.1
XS GIS Cut Line= 4
2114900.31646095313038.6275940352114978.35369645313225.647865332
 2115204.3925855313326.5580836582115286.46622974313379.031397187
#Sta/Elev= 30
       0 1961.62    27.2  1961.1    52.1 1959.62    66.3 1958.28      77 1958.09
   112.5 1953.92   133.8 1949.43   144.5 1948.88   162.8 1947.16   183.6 1942.97
   194.3 1942.35   207.8  1943.1   232.1 1942.81   239.2 1942.29   246.4 1942.92
   261.8 1943.19  289.051938.435   294.1 1937.33  304.761938.433     314 1940.46
   331.4 1941.31   336.3 1941.38   357.8 1939.99   390.1 1940.89   405.9  1943.5
   422.5 1944.55   455.6 1949.18   504.3 1954.36   517.5 1956.57547.6035 1959.46
#Mann= 3 ,-1 , 0
       0      .1       0  289.05    .045       0  304.76      .1       0
#XS Ineff= 2 , 0
             279    1947     314            1947
Permanent Ineff=
       F       F
Bank Sta=289.05,304.76
XS Rating Curve= 0 ,0
Exp/Cntr(USF)=0,0
Exp/Cntr=0.5,0.3