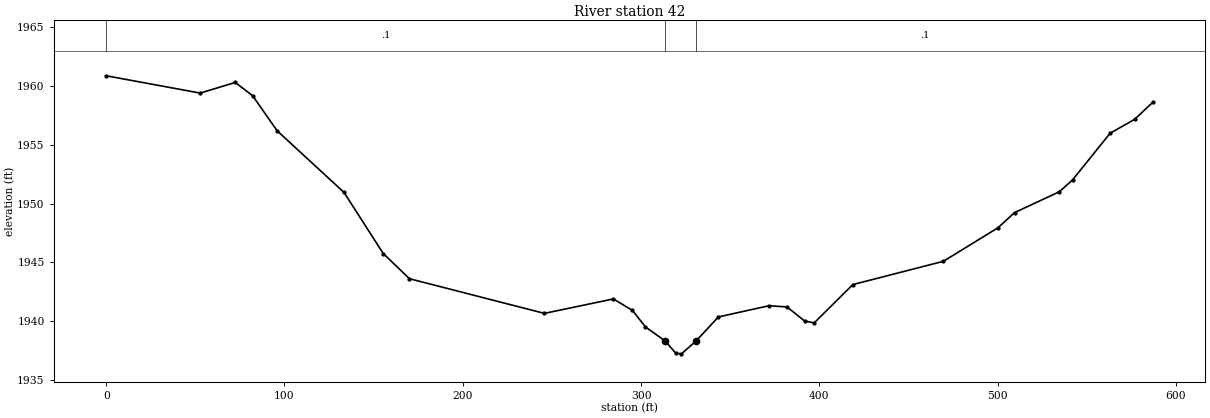
HEC-RAS study MLGNCKTR3.prj: MLGNCKTR3

--- MLGNCKTR3.g01 (geometry) --- (continued)

Type RM Length L Ch R = 1 ,42      ,41.12,42,41.23
XS GIS Cut Line= 4
 2114861.2978432313049.3913506562114964.89900068313256.593665619
2115096.07985732313302.3172572622115291.99114845313394.784008894
#Sta/Elev= 30
       0 1960.88    52.7 1959.41    72.4 1960.31    82.1 1959.19    95.9  1956.2
   133.4 1950.96   155.4 1945.76   170.1 1943.62   245.8 1940.67   284.5  1941.9
   295.2 1940.92   302.5 1939.52  313.541938.321   319.5 1937.28   322.7 1937.23
  330.861938.322   343.4 1940.37   371.7 1941.32   381.9 1941.22   391.7 1940.03
   397.1 1939.86   418.8 1943.12   469.6  1945.1   500.2 1947.95   509.5 1949.24
   534.7 1951.02   542.1 1952.03   563.1 1955.99   576.9 1957.18587.2167 1958.65
#Mann= 3 ,-1 , 0
       0      .1       0  313.54    .045       0  330.86      .1       0
Bank Sta=313.54,330.86
XS Rating Curve= 0 ,0
Exp/Cntr(USF)=0,0
Exp/Cntr=0.3,0.1
Stream Node=BIGCLEARCK      ,Main            , 0 , 0 ,Upstream end
Stream Node=BIGCLEARCK      ,Main            , 0 , 1 ,Downstream end
Stream Node=BROADRN         ,Main            , 0 , 0 ,Upstream end
Stream Node=BROADRN         ,Main            , 0 , 1 ,Downstream end
Stream Node=LAURELBR        ,Main            , 0 , 0 ,Upstream end
Stream Node=LAURELBR        ,Main            , 0 , 1 ,Downstream end
Stream Node=LAURELCK1       ,Main            , 0 , 0 ,Upstream end
Stream Node=LAURELCK1       ,Main            , 0 , 1 ,Downstream end
Stream Node=MEADOWRV3       ,Main            , 0 , 0 ,Upstream end
Stream Node=MEADOWRV3       ,Main            , 0 , 1 ,Downstream end
Stream Node=MEADOWRV4       ,Main            , 0 , 0 ,Upstream end
Stream Node=MEADOWRV4       ,Main            , 0 , 1 ,Downstream end
Stream Node=MLGNCK          ,Main            , 0 , 0 ,Upstream end
Stream Node=MLGNCK          ,Main            , 0 , 1 ,Downstream end
Stream Node=MLGNCKTR3       ,Main            , 0 , 0 ,Upstream end
Stream Node=MLGNCKTR3       ,Main            , 0 , 1 ,Downstream end
Stream Node=MLGNCKTR4       ,Main            , 0 , 0 ,Upstream end
Stream Node=MLGNCKTR4       ,Main            , 0 , 1 ,Downstream end
Stream Node=MUDDYCK         ,Main            , 0 , 0 ,Upstream end
Stream Node=MUDDYCK         ,Main            , 0 , 1 ,Downstream end
Stream Node=SECONDCK        ,Main            , 0 , 0 ,Upstream end
Stream Node=SECONDCK        ,Main            , 0 , 1 ,Downstream end
Stream Node=TUCKHORN        ,Main            , 0 , 0 ,Upstream end
Stream Node=TUCKHORN        ,Main            , 0 , 1 ,Downstream end
Stream Node=TUCKHORNT2      ,Main            , 0 , 0 ,Upstream end
Stream Node=TUCKHORNT2      ,Main            , 0 , 1 ,Downstream end
LCMann Table=0

Chan Stop Cuts=-1
Use User Specified Reach Order=0
Composite Channel Slope=5